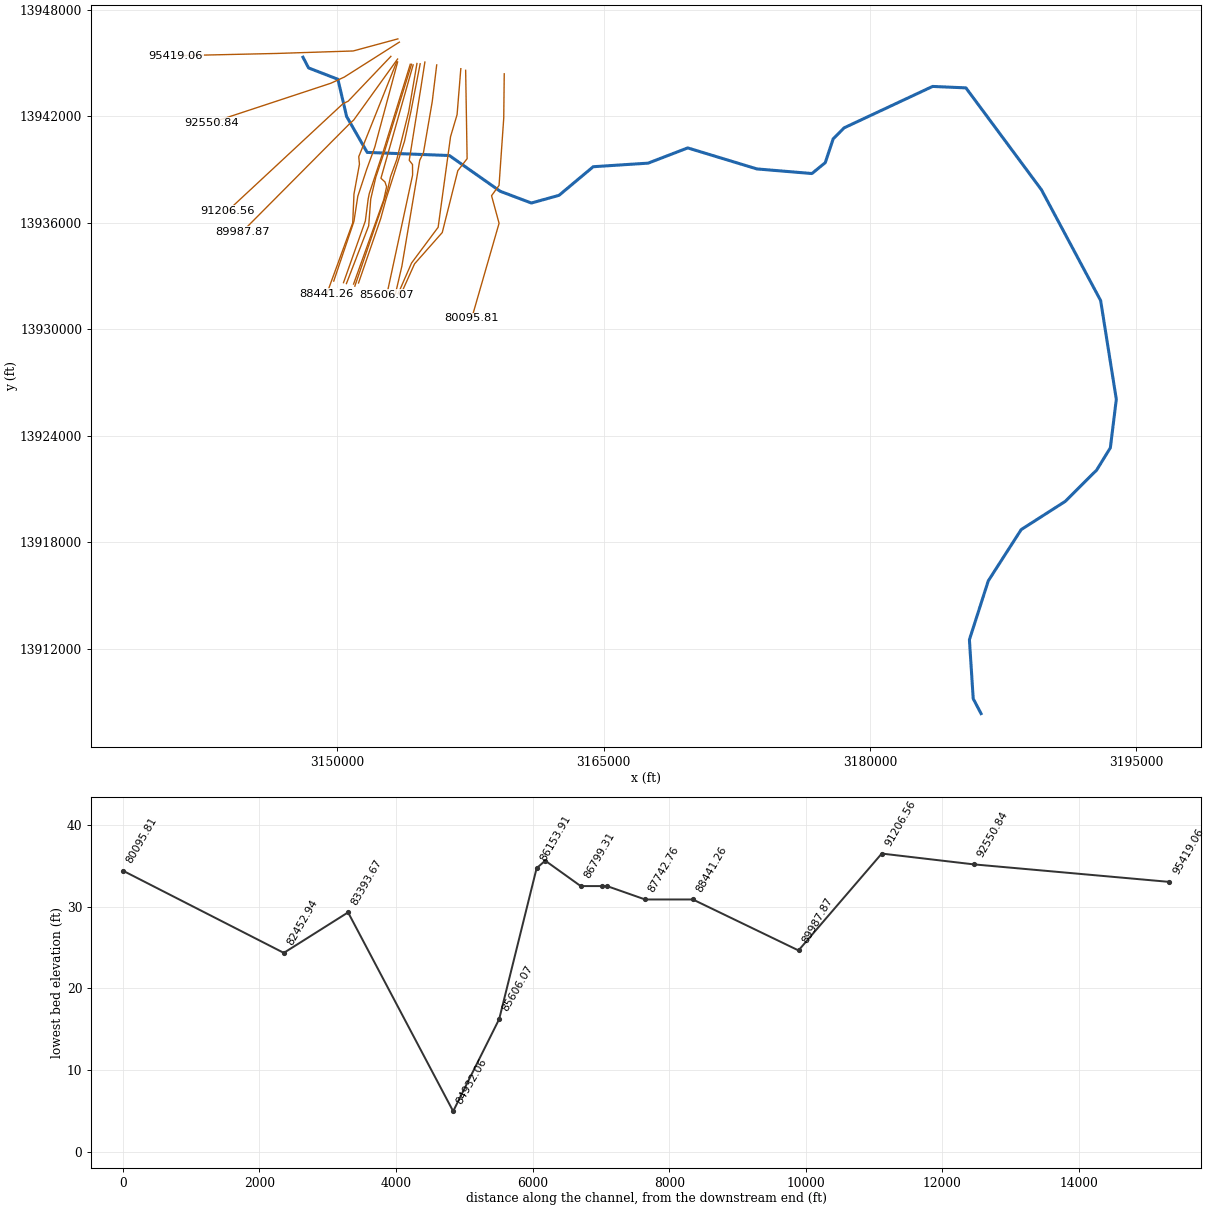
--- G103-00-00WFSJ.prj (project) ---

Proj Title=G103-00-00WFSJ
Current Plan=p10
Default Exp/Contr=.3,.1
English Units
Geom File=g05
Flow File=f01
Flow File=f02
Plan File=p10
Plan File=p09
Y Axis Title=Elevation
X Axis Title(PF)=Main Channel Distance
X Axis Title(XS)=Station
BEGIN DESCRIPTION:
San Jacinto River Watershed
West Fork San Jacinto River
HCFCD unit G103-00-00
(Flood Hazard, Floodway)Model
10, 2, 1, 0.2% Event
Filename G1030000wfsj.prj
Prepared by:  FTN Associates Ltd.   DATE:  February 2003
EDITED:  August 2004
Reviewed by:     DATE:
The boundary condition is known water surface elevation at the downstream end, obtained from the Lake Houston model. WSEl of 45.67, 48.56, 49.99, 54.12 are used for the 10, 50, 100 and 500yr profiles respectively (10%, 2%, 1%, and .2% annual chance).
The geometry for the cross sections is based on survey data except at section 44044.71, where the  effective FIS HEC-2 (9/10/87) data for Lake Houston, adjusted for subsidence, is used. This is a common section for Lake Houston and WF San jacincto to obtain the WSELs from the Lake Houston model as the boundary condition.
Flows from 1979 FIS HEC2 data. Stationing from HEC2 data had to be adjusted +26216 ft for input to current model (based on location of Hwy. 59 bridges).
Section 44044.71 is located a common section to Lake Houston RS 48519.40 (lh8p67), so the survey data are used in that section.
The known water surface elevation of 50.88' comes from the computed floodway elevation  of Lake Houston at the common section.
END DESCRIPTION:
DSS Export Rating Curves= 0
DSS Export Rating Curve Sorted= 0
DSS Export Volume Flow Curves= 0
DXF OffsetX= 0
DXF OffsetY= 0
DXF ScaleX= 1
DXF ScaleY= 10

--- G103-00-00WFSJ.p10 (plan) ---

Plan Title=FEMA Effective June 2010
Version=Version 3.0.1  Mar 2001
Short Identifier=MP
Geom File=g05
Flow File=f01
Subcritical Flow
K Sum by GR= 0
Std Step Tol= 0.01
Critical Tol= 0.01
Num of Std Step Trials= 20
Max Error Tol= 0.3
Flow Tol Ratio= 0.001
Split Flow NTrial= 30
Split Flow Tol= 0.02
Split Flow Ratio= 0.02
Log Output Level= 0
Friction Slope Method= 1
Unsteady Friction Slope Method= 2
Parabolic Critical Depth
Global Vel Dist= 0 , 0 , 0
Global Log Level= 0
CheckData=True
Encroach Param=-1 ,0,0, 0
BEGIN DESCRIPTION:
FEMA Effective June 2007 + LOMR 07-06-2162P + LOMR 08-06-0712P.
END DESCRIPTION:
Computation Interval=1HOUR
Output Interval=1HOUR
Run HTab= 0
Run UNet= 0
Run PostProcess= 0
UNET Theta= 1
UNET ZTol= 0.02
UNET ZSATol= 0.1
UNET MxIter= 20
UNET MaxInSteps= 20
UNET DtIC= 0
UNET DtMin= 0
UNET MaxCRTS= 20
UNET WFStab= 2
UNET SFStab= 1
UNET WFX= 1
UNET SFX= 1
UNET Convert EG Bridges=-1
UNET Use Existing IB Tables=-1
Instantaneous Interval=1HOUR
Write IC File= 0
Write Velocity= 0
Write Detailed= 0

--- G103-00-00WFSJ.p07 (plan) ---

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Plan Title=LOMR 08-06-0712P Floodway
Short Identifier=0712 FW
Geom File=g01
Flow File=f02

--- G103-00-00WFSJ.p09 (plan) ---

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Plan Title=Floodway
Short Identifier=FW
Geom File=g05
Flow File=f02
Encroach Param=-1 ,0,0, 2
Encroach River=G103-00-00WFSJ
Encroach Reach=G1030000WF_0440
Encroach Node=95419.06
       1    2548    6480
Encroach Node=92550.84
       1    3566    6559
Encroach Node=91206.56
       1    3011    6976
Encroach Node=89987.87
       1    3258    7020
Encroach Node=88441.26
       1    3650    6400
Encroach Node=87742.76
       1 4620.08  6174.7
Encroach Node=87463.61
       1 4620.08  6174.7
Encroach Node=87184.46
       1 4620.08  6174.7
Encroach Node=87112.78
       1    4362    7875
Encroach Node=86799.31
       1    4000    8250
Encroach Node=86280.02
       1    3800    8200
Encroach Node=86216.96
       1    3800    8200
Encroach Node=86153.91
       1    3800    8200
Encroach Node=85606.07
       1    3600    7200
Encroach Node=84932.06
       1    3428    7150
Encroach Node=83393.67
       1    3836    9350
Encroach Node=82452.94
       1    3467    9703
Encroach Node=80095.81
       1    4365   10308
Encroach Node=78212.09
       1    466913069.99
Encroach Node=74800.67
       1    1886    7711
Encroach Node=72784.57
       1    5550   11934
Encroach Node=70613.72
       1    5563   10969
Encroach Node=69395.08
       1    5870    9950
Encroach Node=68690.36
       1    6200   11500
Encroach Node=64969.45
       1    6000   10778
Encroach Node=61563.42
       1    690010847.35
Encroach Node=58206.30
       1    9745   13113
Encroach Node=58060.89
       1    9745   13113
Encroach Node=57915.48
       1   10049   13383
Encroach Node=56153.38
       1   10245   13512
Encroach Node=52026.90
       1    1679    5871
Encroach Node=44044.71
       1    138710107.83

--- G103-00-00WFSJ.f01 (steady flow) ---

Flow Title=FEMA Effective June 2007
Version=Version 3.0.1  Mar 2001
Number of Profiles= 4
Profile Names=10PCT_10yr, 2PCT_50yr, 1PCT_100yr, 0.2PCT_500yr
River Rch & RM=G103-00-00WFSJ,G1030000WF_0440 ,95419.06
   61130  123080  165730  299930
River Rch & RM=G103-00-00WFSJ,G1030000WF_0440 ,88441.26
   62300  127200  167500  306000
River Rch & RM=G103-00-00WFSJ,G1030000WF_0440 ,87112.78
   62340  127340  167560  307140
River Rch & RM=G103-00-00WFSJ,G1030000WF_0440 ,86799.31
   62410  127600  167670  307570
River Rch & RM=G103-00-00WFSJ,G1030000WF_0440 ,85606.07
   62560  128120  167890  308450
River Rch & RM=G103-00-00WFSJ,G1030000WF_0440 ,84932.06
   62690  128570  168090  310160
River Rch & RM=G103-00-00WFSJ,G1030000WF_0440 ,83393.67
   62850  129130  168330  309220
River Rch & RM=G103-00-00WFSJ,G1030000WF_0440 ,82452.94
   63510  131460  169330  314100
River Rch & RM=G103-00-00WFSJ,G1030000WF_0440 ,74800.67
   63800  132480  169770  315820
River Rch & RM=G103-00-00WFSJ,G1030000WF_0440 ,70613.72
   64610  135320  171000  320030
River Rch & RM=G103-00-00WFSJ,G1030000WF_0440 ,64969.45
   64830  136080  171320  321900
River Rch & RM=G103-00-00WFSJ,G1030000WF_0440 ,61563.42
   65680  139080  172610  326970
River Rch & RM=G103-00-00WFSJ,G1030000WF_0440 ,56153.38
   66160  140750  173330  329800
River Rch & RM=G103-00-00WFSJ,G1030000WF_0440 ,52026.90
   66800  143000  174300  333600
River Rch & RM=G103-00-00WFSJ,G1030000WF_0440 ,44044.71
   75056  160681  214619  369116
Boundary for River Rch & Prof#=G103-00-00WFSJ,G1030000WF_0440 , 1
Up Type= 0
Dn Type= 1
Dn Known WS=45.67
Boundary for River Rch & Prof#=G103-00-00WFSJ,G1030000WF_0440 , 2
Up Type= 0
Dn Type= 1
Dn Known WS=48.56
Boundary for River Rch & Prof#=G103-00-00WFSJ,G1030000WF_0440 , 3
Up Type= 0
Dn Type= 1
Dn Known WS=49.99
Boundary for River Rch & Prof#=G103-00-00WFSJ,G1030000WF_0440 , 4
Up Type= 0
Dn Type= 1
Dn Known WS=54.12
Observed WS=G103-00-00WFSJ  ,G1030000WF_0440 ,87184.46, 0 ,,,67.2,67.2
Observed WS=G103-00-00WFSJ  ,G1030000WF_0440 ,87112.78, 0 ,,,65.9,65.9
Observed WS=G103-00-00WFSJ  ,G1030000WF_0440 ,74800.67, 0 ,,,59,59
Observed WS=G103-00-00WFSJ  ,G1030000WF_0440 ,72784.57, 0 ,,,57.2,57.2
Observed WS=G103-00-00WFSJ  ,G1030000WF_0440 ,70613.72, 0 ,,,56.8,56.8
Observed WS=G103-00-00WFSJ  ,G1030000WF_0440 ,68690.36, 0 ,,,56.4,56.4
Observed WS=G103-00-00WFSJ  ,G1030000WF_0440 ,58206.30, 0 ,,,,
Observed WS=G103-00-00WFSJ  ,G1030000WF_0440 ,57915.48, 0 ,,,54.3,54.3
Observed WS=G103-00-00WFSJ  ,G1030000WF_0440 ,52026.90, 0 ,,,52.3,52.3
DSS Import GetInterval= 0
DSS Import GetPeak= 0
DSS Import FillOption= 0

--- G103-00-00WFSJ.f02 (steady flow) ---

Flow Title=Floodway
Version=Version 3.0.1  Mar 2001
Number of Profiles= 2
Profile Names=1PCT_100yr,Floodway
River Rch & RM=G103-00-00WFSJ,G1030000WF_0440 ,95419.06
  165730  165730
River Rch & RM=G103-00-00WFSJ,G1030000WF_0440 ,88441.26
  167500  167500
River Rch & RM=G103-00-00WFSJ,G1030000WF_0440 ,87112.78
  167560  167560
River Rch & RM=G103-00-00WFSJ,G1030000WF_0440 ,86799.31
  167670  167670
River Rch & RM=G103-00-00WFSJ,G1030000WF_0440 ,85606.07
  167890  167890
River Rch & RM=G103-00-00WFSJ,G1030000WF_0440 ,84932.06
  168090  168090
River Rch & RM=G103-00-00WFSJ,G1030000WF_0440 ,83393.67
  168330  168330
River Rch & RM=G103-00-00WFSJ,G1030000WF_0440 ,82452.94
  169330  169330
River Rch & RM=G103-00-00WFSJ,G1030000WF_0440 ,74800.67
  169770  169770
River Rch & RM=G103-00-00WFSJ,G1030000WF_0440 ,70613.72
  171000  171000
River Rch & RM=G103-00-00WFSJ,G1030000WF_0440 ,64969.45
  171320  171320
River Rch & RM=G103-00-00WFSJ,G1030000WF_0440 ,61563.42
  172610  172610
River Rch & RM=G103-00-00WFSJ,G1030000WF_0440 ,56153.38
  173330  173330
River Rch & RM=G103-00-00WFSJ,G1030000WF_0440 ,52026.90
  174300  174300
River Rch & RM=G103-00-00WFSJ,G1030000WF_0440 ,44044.71
  214619  214619
Boundary for River Rch & Prof#=G103-00-00WFSJ,G1030000WF_0440 , 1
Up Type= 0
Dn Type= 1
Dn Known WS=49.99
Boundary for River Rch & Prof#=G103-00-00WFSJ,G1030000WF_0440 , 2
Up Type= 0
Dn Type= 1
Dn Known WS=50.88
Observed WS=G103-00-00WFSJ  ,G1030000WF_0440 ,87184.46, 0 ,,
Observed WS=G103-00-00WFSJ  ,G1030000WF_0440 ,87112.78, 0 ,,
Observed WS=G103-00-00WFSJ  ,G1030000WF_0440 ,74800.67, 0 ,,
Observed WS=G103-00-00WFSJ  ,G1030000WF_0440 ,72784.57, 0 ,,
Observed WS=G103-00-00WFSJ  ,G1030000WF_0440 ,70613.72, 0 ,,
Observed WS=G103-00-00WFSJ  ,G1030000WF_0440 ,68690.36, 0 ,,
Observed WS=G103-00-00WFSJ  ,G1030000WF_0440 ,58206.30, 0 ,,
Observed WS=G103-00-00WFSJ  ,G1030000WF_0440 ,57915.48, 0 ,,
Observed WS=G103-00-00WFSJ  ,G1030000WF_0440 ,52026.90, 0 ,,
DSS Import GetInterval= 0
DSS Import GetPeak= 0
DSS Import FillOption= 0

--- G103-00-00WFSJ.g05 (geometry) ---

Geom Title=G103-00-00WFSJ June 2010
Version=Version 3.0.1  Mar 2001

River Reach=G103-00-00WFSJ  ,G1030000WF_0440
Reach XY= 30
     3148069.672    13945320.192     3148385.034    13944717.504
     3150036.097    13944077.746      3150527.91    13941982.438
     3151685.901    13939960.113     3156313.438    13939783.667
     3159177.326    13937770.726     3160932.289    13937108.752
     3162490.074    13937542.801     3164415.816    13939153.385
     3167506.171    13939354.804     3169738.304    13940212.115
     3173635.566    13939028.569     3176732.934    13938769.847
      3177484.47    13939383.297     3177928.254    13940720.343
     3178548.315    13941344.247     3183529.381    13943674.862
      3185404.75       13943594.      3189658.75       13937854.
        3192992.       13931617.        3193875.       13926054.
      3193539.25       13923323.       3192769.5       13922071.
        3190996.       13920304.      3188517.75       13918717.
       3186664.5       13915830.        3185602.       13912517.
        3185816.       13909194.     3186257.683    13908355.244

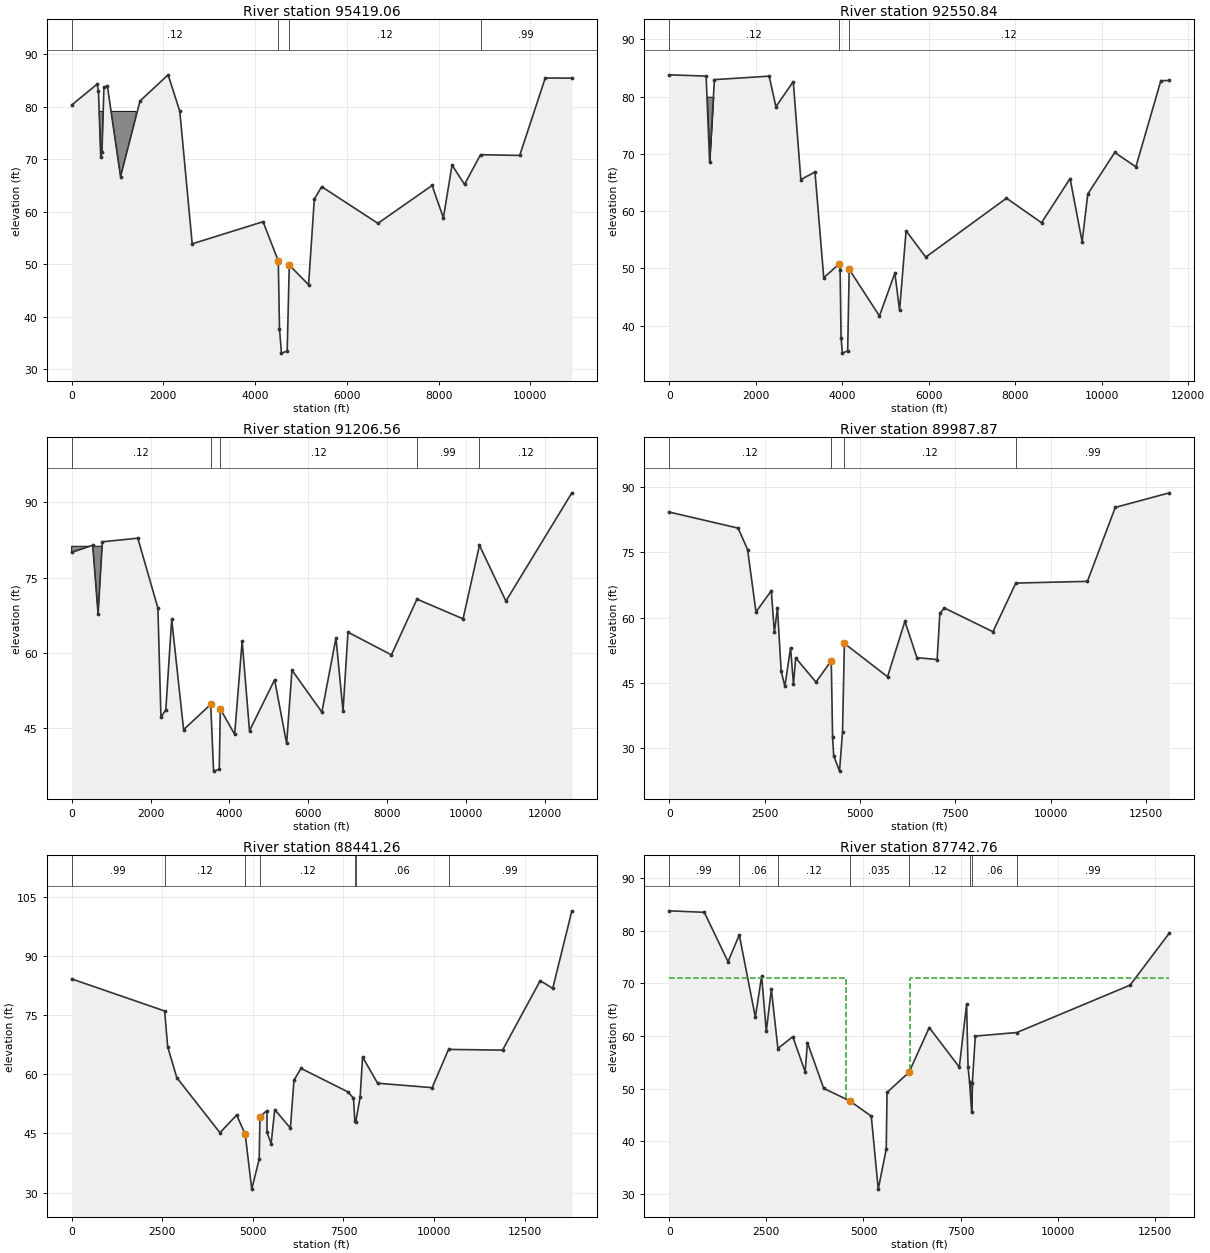
Type RM Length L Ch R = 1 ,95419.06,1425.61,2868.23,2659.04
BEGIN DESCRIPTION:
Copy of 421v1
(Inverts adjusted based off of slope from the FIS profile.)
END DESCRIPTION:
XS GIS Cut Line= 5
     3153414.256    13946352.802     3150897.242       13945672.
      3150841.49       13945670.     3146606.741       13945533.
      3140916.99       13945405.
#Sta/Elev= 30
       0   80.35 552.905   84.31 583.987    83.1 633.645   70.44 660.561   71.38
 703.317   83.79 779.007   83.961065.142   66.711490.083   81.132102.017   86.11
2357.104   79.162627.365   53.884171.645    58.14504.501   50.614530.188   37.73
4572.674   33.044697.876   33.434743.784   49.835164.404   46.095290.186   62.42
5450.564   64.786676.363   57.79 7856.86   65.018103.478   58.848291.864    68.9
8563.935   65.228913.056   70.889767.649   70.7410323.97    85.510904.48   85.48
#Mann= 4 ,-1 , 0
       0     .12       04504.501     .03       04743.784     .12       0
8913.056     .99       0
#Block Obstruct= 2 , 0
       01405.906   79.14               0
Bank Sta=4504.501,4743.784
XS Rating Curve= 0
Skew Angle= 30
Exp/Cntr=.3,.1

Type RM Length L Ch R = 1 ,92550.84,1105.75,1343.98,2160.35
BEGIN DESCRIPTION:
Copy of 421v1
(Inverts adjusted based off of slope from the FIS profile.)
END DESCRIPTION:
XS GIS Cut Line= 4
     3153496.961    13946170.288     3150401.268    13944204.829
     3149635.952    13943853.683     3142936.684    13941643.615
#Sta/Elev= 30
       0   83.82  853.32    83.6  934.59   68.64 1045.43   82.98 2311.21   83.59
 2466.81   78.24 2868.47   82.64 3042.73   65.52 3370.11   66.84 3572.64   48.37
 3934.79    50.8 3951.12   49.793972.836   37.924002.965   35.194125.974   35.58
 4161.17   49.83 4860.32   41.68  5217.1   49.18 5325.57   42.68 5476.09   56.57
  5930.8   51.97 7797.48   62.26 8607.64   57.98 9267.84   65.69 9546.11   54.65
  9676.7   62.9910299.61   70.2510788.59   67.7511365.52   82.7911563.36   82.84
#Mann= 3 , 0 , 0
       0     .12       0 3934.79     .03       0 4161.17     .12       0
#Block Obstruct= 2 , 0
       0 1037.36      80               0
Bank Sta=3934.79,4161.17
XS Rating Curve= 0
Exp/Cntr=.3,.1

Type RM Length L Ch R = 1 ,91206.56,874.34,1218.7,1139.82
BEGIN DESCRIPTION:
421v1
Bank Station offset =      1402
END DESCRIPTION:
XS GIS Cut Line= 4
      3153020.02     13945367.53     3150617.371    13942846.575
     3150315.436    13942696.834     3143822.584    13936660.114
#Sta/Elev= 30
       0   80.02   533.7   81.43  669.74   67.78  778.45   82.12 1677.11   82.84
 2186.37   68.94 2264.23    47.2 2387.33   48.74 2536.49   66.68 2838.49   44.76
 3526.48   49.79 3598.44   36.51 3743.01    36.9 3769.29   48.89 4132.88   43.82
 4323.16   62.38 4509.94   44.53 5146.22   54.67 5451.39   42.01 5586.81   56.59
 6344.72   48.25 6702.78   62.98 6881.52   48.44  7006.9   64.15 8109.21   59.63
 8756.68   70.72 9925.67    66.810341.58   81.4111013.16   70.3312685.17   91.86
#Mann= 5 ,-1 , 0
       0     .12       0 3526.48     .03       0 3769.29     .12       0
 8756.68     .99       010341.58     .12       0
#Block Obstruct= 2 , 0
       0  775.29   81.24   10336       0    81.5
Bank Sta=3526.48,3769.29
XS Rating Curve= 0
Exp/Cntr=.3,.1

Type RM Length L Ch R = 1 ,89987.87,1273.25,1546.6,2095.39
BEGIN DESCRIPTION:
421v2
Bank Station offset =       534
END DESCRIPTION:
XS GIS Cut Line= 4
     3153396.973    13945216.753     3150930.538    13941788.492
     3150642.421     13941521.56     3144651.862    13935491.586
#Sta/Elev= 30
       0   84.27  1806.8   80.57 2055.15   75.64 2276.06   61.28 2677.13   66.17
 2757.34   56.57  2838.8   62.17 2935.53   47.69 3033.08   44.17 3182.35   53.03
 3257.93   44.69 3317.29   50.71 3847.58   45.14 4249.56   50.04 4284.48    32.4
 4314.26   28.16 4465.96   24.65 4544.75   33.67 4593.47   54.04  5725.3   46.36
 6180.41   59.13 6495.16   50.76 7026.06   50.33 7096.96   60.95 7216.11   62.19
 8489.29   56.72 9089.13   67.9210966.22   68.3211696.91   85.3413115.92   88.69
#Mann= 4 ,-1 , 0
       0     .12       0 4249.56     .03       0 4593.47     .12       0
 9089.13     .99       0
Bank Sta=4249.56,4593.47
XS Rating Curve= 0
Exp/Cntr=.3,.1

Type RM Length L Ch R = 1 ,88441.26,861.43,698.51,487.03
BEGIN DESCRIPTION:
Copy of 421s7u.  XS 4/4
Blocked Trib 17.7 422s2u channel cross section between stations 7814.84 and 7836.65.  Manning's n is set to 0.01 to represent flow over water in this area.
Bank Station offset =        31
END DESCRIPTION:
XS GIS Cut Line= 6
      3153352.71    13945072.128     3151211.395     13939717.87
     3151249.232    13939294.313     3150941.922     13937616.57
     3150871.324    13935992.813     3149405.759    13931981.801
#Sta/Elev= 30
       0   84.19 2566.19   76.06 2649.11   66.98 2900.33   59.17 4092.25   45.19
 4553.42   49.69 4789.93   44.76 4969.01   30.89 5175.17   38.51 5195.82   49.28
 5389.38    50.8 5391.31   45.25 5504.89   42.46  5604.3   51.06 6035.55   46.37
 6135.11   58.52 6328.76   61.51 7624.73   55.54 7777.19   53.97 7814.84   48.05
 7836.65   47.85    7960   54.19 8028.15    64.4 8441.73   57.75 9947.44   56.62
10400.74   66.3211890.54   66.1412930.21   83.7513275.37   81.7913803.84  101.46
#Mann= 7 ,-1 , 0
       0     .99       0 2566.19     .12       0 4789.93    .035       0
 5195.82     .12       0 7814.84     .01       0 7836.65     .06       0
10400.74     .99       0
#Block Obstruct= 2 ,-1
 7814.84 7836.65   47.85   11560   11855    65.8
Bank Sta=4789.93,5195.82
XS Rating Curve= 0
Exp/Cntr=.5,.3

Type RM Length L Ch R = 1 ,87742.76,551.06,558.29,571.7
BEGIN DESCRIPTION:
421s7u - surveyed, XS 3/4
Blocked Trib 17.7 422s3u channel cross section between stations 7731.22 and 7801.83.  Manning's n is set to 0.01 to represent flow over water in this area.
Ineffective 0.99 set for 0.2% chance flow due to contraction from ineffective 0.99 of this flow on d/s side of bridge (XS 2/4)
Bank Station offset =      -380
END DESCRIPTION:
XS GIS Cut Line= 6
     3153400.389    13945052.782     3152112.003     13940250.84
     3151660.421    13939012.018     3151157.376    13937487.866
     3150941.062    13936080.444     3149802.157     13932712.69
#Sta/Elev= 30
       0   83.79  903.48   83.51 1514.34   74.12 1803.75   79.22 2217.35   63.58
 2379.89   71.39 2498.36   60.88 2628.84   68.87 2797.79   57.62 3181.23   59.87
 3498.82    53.2 3558.49   58.74 3976.15   50.05 4644.16   47.68 5201.31   44.76
 5380.39   30.89 5586.55   38.51  5607.2   49.28  6174.7   53.11 6692.93    61.6
 7467.25   54.08 7654.77   66.04  7692.4   54.03 7731.22   51.28 7784.26   45.51
 7801.83   51.02 7878.87   59.98 8948.43   60.6611864.11   69.6712874.54   79.58
#Mann= 8 ,-1 , 0
       0     .99       0 1803.75     .06       0 2797.79     .12       0
 4644.16    .035       0  6174.7     .12       0 7731.22     .01       0
 7801.83     .06       0 8948.43     .99       0
#XS Ineff= 2 , 0
       0    4550   71.06    6200       0   71.06
Permanent Ineff=
       F       F
#Block Obstruct= 1 ,-1
 7731.22 7801.83   51.02
Bank Sta=4644.16,6174.7
XS Rating Curve= 0
Exp/Cntr=.5,.3

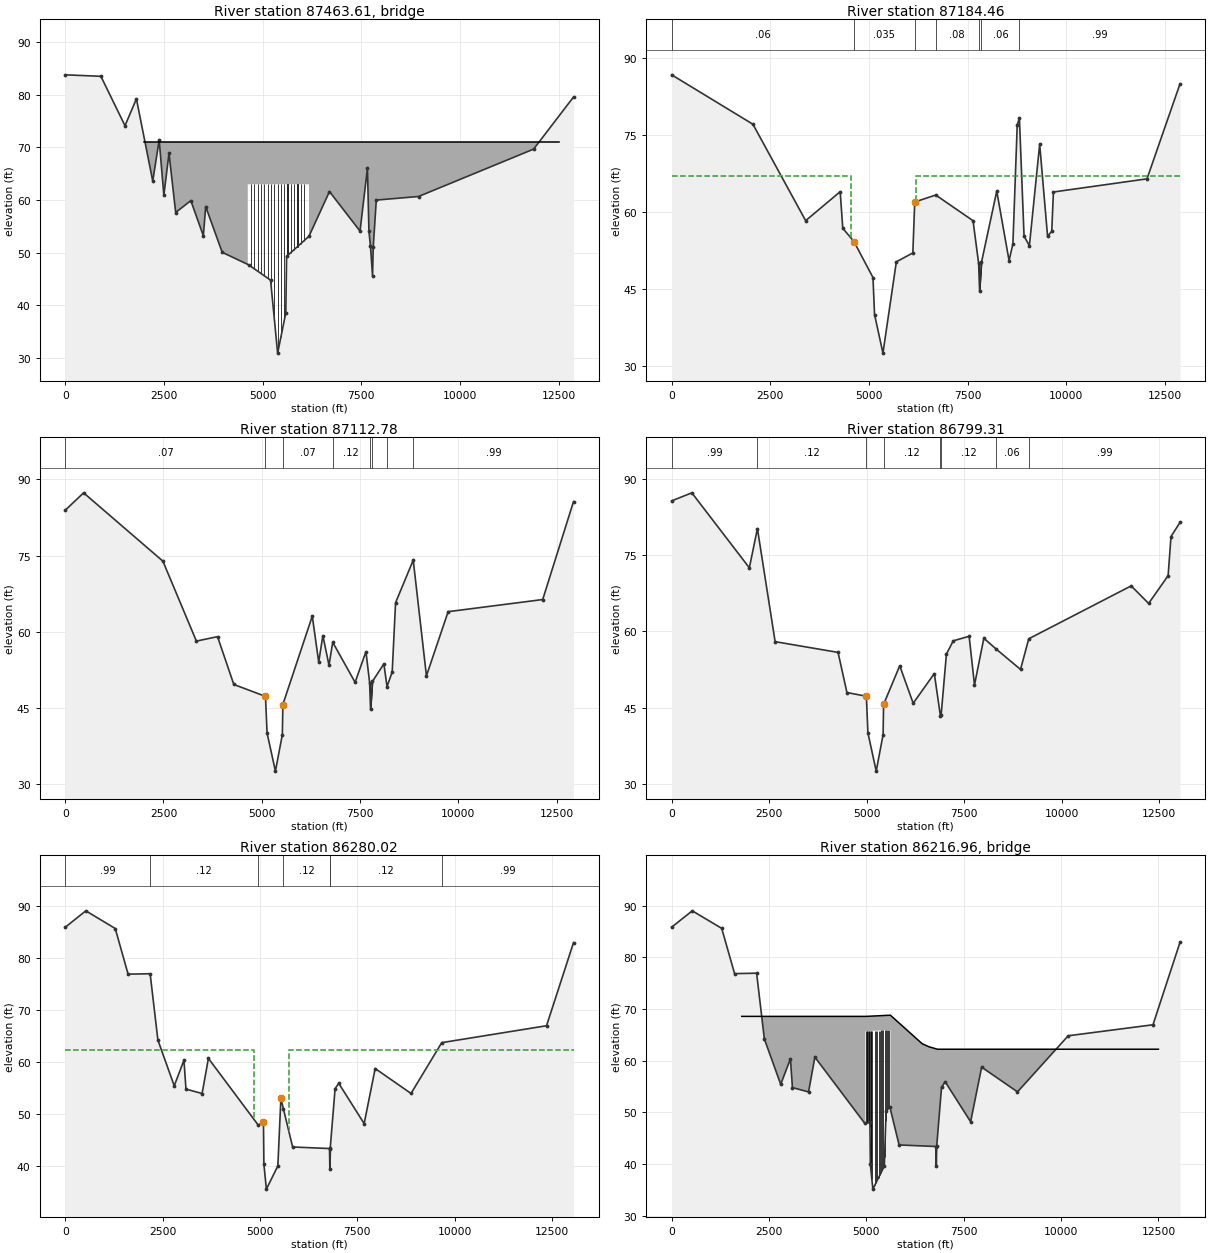
Type RM Length L Ch R = 3 ,87463.61,,,
BEGIN DESCRIPTION:
 421s3-421s7
US Hwy 59, northbound, southbound, access roads & ramps.
END DESCRIPTION:
Bridge Culvert--1,0,-1,-1, 0
Deck Dist Width WeirC Skew NumUp NumDn MinLoCord MaxHiCord MaxSubmerge Is_Ogee
15.65,527,2.6,0, 6, 6, , , .95, 0, 0,0,,
    2000 4623.84 4623.84 6175.27 6175.27   12500
   71.06   71.06   71.06   71.06   71.06   71.06
       0       0   62.98   62.98       0       0
    2000 4623.84 4623.84 6175.27 6175.27   12500
   71.06   71.06   71.06   71.06   71.06   71.06
       0       0   62.98   62.98       0       0
Pier Skew, UpSta & Num, DnSta & Num=  ,4707.62, 4 ,4707.62, 4 , 3 , 3 , 0 ,,
       3       3       4       4
      30   58.98   58.98   62.98
       3       3       4       4
      30   58.98   58.98   62.98
Pier Skew, UpSta & Num, DnSta & Num=  ,4791.57, 4 ,4791.57, 4 , 3 , 3 , 0 ,,
       3       3       4       4
      30   58.98   58.98   62.98
       3       3       4       4
      30   58.98   58.98   62.98
Pier Skew, UpSta & Num, DnSta & Num=  ,4875.51, 4 ,4875.51, 4 , 3 , 3 , 0 ,,
       3       3       4       4
      30   58.98   58.98   62.98
       3       3       4       4
      30   58.98   58.98   62.98
Pier Skew, UpSta & Num, DnSta & Num=  ,4959.6, 4 ,4959.6, 4 , 3 , 3 , 0 ,,
       3       3       4       4
      30   58.98   58.98   62.98
       3       3       4       4
      30   58.98   58.98   62.98
Pier Skew, UpSta & Num, DnSta & Num=  ,5043.64, 4 ,5043.64, 4 , 3 , 3 , 0 ,,
       3       3       4       4
      30   58.98   58.98   62.98
       3       3       4       4
      30   58.98   58.98   62.98
Pier Skew, UpSta & Num, DnSta & Num=  ,5127.39, 4 ,5127.39, 4 , 3 , 3 , 0 ,,
       3       3       4       4
      30   58.98   58.98   62.98
       3       3       4       4
      30   58.98   58.98   62.98
Pier Skew, UpSta & Num, DnSta & Num=  ,5211.79, 4 ,5211.79, 4 , 3 , 3 , 0 ,,
       3       3       4       4
      30   58.98   58.98   62.98
       3       3       4       4
      30   58.98   58.98   62.98
Pier Skew, UpSta & Num, DnSta & Num=  ,5295.82, 4 ,5295.82, 4 , 3 , 3 , 0 ,,
       3       3       4       4
      30   58.98   58.98   62.98
       3       3       4       4
      30   58.98   58.98   62.98
Pier Skew, UpSta & Num, DnSta & Num=  ,5379.5, 4 ,5379.5, 4 , 3 , 3 , 0 ,,
       3       3       4       4
      30   58.98   58.98   62.98
       3       3       4       4
      30   58.98   58.98   62.98
Pier Skew, UpSta & Num, DnSta & Num=  ,5463.7, 4 ,5463.7, 4 , 3 , 3 , 0 ,,
       3       3       4       4
      30   58.98   58.98   62.98
       3       3       4       4
      30   58.98   58.98   62.98
Pier Skew, UpSta & Num, DnSta & Num=  ,5547.63, 4 ,5547.63, 4 , 3 , 3 , 0 ,,
       3       3       4       4
      30   58.98   58.98   62.98
       3       3       4       4
      30   58.98   58.98   62.98
Pier Skew, UpSta & Num, DnSta & Num=  ,5631.55, 4 ,5631.55, 4 , 3 , 3 , 0 ,,
       3       3       4       4
      30   58.98   58.98   62.98
       3       3       4       4
      30   58.98   58.98   62.98
Pier Skew, UpSta & Num, DnSta & Num=  ,5715.6, 4 ,5715.6, 4 , 3 , 3 , 0 ,,
       3       3       4       4
      30   58.98   58.98   62.98
       3       3       4       4
      30   58.98   58.98   62.98
Pier Skew, UpSta & Num, DnSta & Num=  ,5799.51, 4 ,5799.51, 4 , 3 , 3 , 0 ,,
       3       3       4       4
      30   58.98   58.98   62.98
       3       3       4       4
      30   58.98   58.98   62.98
Pier Skew, UpSta & Num, DnSta & Num=  ,5883.75, 4 ,5883.75, 4 , 3 , 3 , 0 ,,
       3       3       4       4
      30   58.98   58.98   62.98
       3       3       4       4
      30   58.98   58.98   62.98
Pier Skew, UpSta & Num, DnSta & Num=  ,5967.55, 4 ,5967.55, 4 , 3 , 3 , 0 ,,
       3       3       4       4
      30   58.98   58.98   62.98
       3       3       4       4
      30   58.98   58.98   62.98
Pier Skew, UpSta & Num, DnSta & Num=  ,6051.53, 4 ,6051.53, 4 , 3 , 3 , 0 ,,
       3       3       4       4
      30   58.98   58.98   62.98
       3       3       4       4
      30   58.98   58.98   62.98
BR Coef=-1 , 1 , 1 ,1.25, 0 ,,,.8,0,2,0,
WSPro=,,,, 1 ,,,, 0 ,,,, 0 ,,,,-1 ,-1 ,-1 , 0 , 0 , 0 , 0 , 0
BC Design=,, 0 ,, 0 ,,,,,,
BC HTab HWMax=84

Type RM Length L Ch R = 1 ,87184.46,67.48,71.68,70.92
BEGIN DESCRIPTION:
Copy of 421s3d  - XS 2.5/4,
Blocked Trib 17.7 422s7d channel cross section between stations 7779.54 and 7851.58.  Manning's n is set to 0.01 to represent flow over water in this area.
Bank Station offset =      -354
END DESCRIPTION:
XS GIS Cut Line= 6
     3154111.681    13944922.145     3152628.489    13940130.036
     3151803.263     13937642.24     3151740.791    13937329.883
     3151581.554    13936095.101     3150352.518    13932624.882
#Sta/Elev= 30
       0   86.71 2059.13   77.09 3395.54   58.32 4270.55   63.96 4336.28   56.84
 4620.08   54.25 5101.55   47.25 5141.61   40.04 5354.23   32.53 5694.24   50.31
  6111.9   52.03 6160.28   61.95 6692.23   63.31 7637.71   58.31 7779.54   49.98
 7803.76   44.69 7851.58    50.2 8238.44   64.06 8551.04   50.54 8648.01   53.81
 8757.68      77 8812.77   78.24 8930.65    55.3 9065.86   53.44 9326.32   73.19
 9526.55   55.28 9632.63   56.25  9674.4    63.912045.99   66.4612882.69   84.95
#Mann= 7 ,-1 , 0
       0     .06       0 4620.08    .035       0 6160.28     .06       0
 6692.23     .08       0 7779.54     .01       0 7851.58     .06       0
 8812.77     .99       0
#XS Ineff= 2 , 0
       0    4550   67.02    6200       0   67.02
Permanent Ineff=
       F       F
#Block Obstruct= 1 ,-1
 7779.54 7851.58   49.98
Bank Sta=4620.08,6160.28
XS Rating Curve= 0
Exp/Cntr=.5,.3

Type RM Length L Ch R = 1 ,87112.78,254.55,313.47,343.56
BEGIN DESCRIPTION:
421s3d, surveyed section.  - XS 2/4,
Blocked WFSJ Trib 17.7 422s7d channel cross section between stations 7744.06 and 7816.1.  Manning's n is set to 0.01 to represent flow over study stream in this area.
Overbank Manning's n value increased from 0.06 to 0.07 to reduce negative slope in 1% annual chance floodplain. The change in WSELs was insignificant.
Bank Station offset =      -348
END DESCRIPTION:
XS GIS Cut Line= 6
     3154181.681    13944922.145     3152698.489    13940130.036
     3152172.786    13938569.599     3151885.198    13937328.956
     3151769.525    13935825.195      3150516.39    13932571.864
#Sta/Elev= 30
       0   83.91  468.09   87.35  2484.9   73.89 3337.32   58.14 3875.03   59.02
 4289.25    49.6 5095.05   47.25 5135.11   40.04 5347.73   32.53 5524.25   39.73
 5536.84   45.65 6285.43   63.06 6449.13      54 6554.27   59.23 6710.65   53.39
 6805.49   57.91  7374.6   50.02 7650.96   56.07 7744.06   49.98 7768.28   44.69
  7816.1    50.2 8106.33   53.65 8187.16   49.18 8318.62   52.07 8404.25    65.7
 8853.64   74.09 9189.44    51.3  9741.8   63.9412147.57   66.3312931.59   85.63
#Mann= 8 ,-1 , 0
       0     .07       0 5095.05     .03       0 5536.84     .07       0
 6805.49     .12       0 7744.06     .01       0  7816.1     .12       0
 8187.16     .07       0 8853.64     .99       0
#Block Obstruct= 1 ,-1
 7744.06  7816.1   49.98
Bank Sta=5095.05,5536.84
XS Rating Curve= 0
Exp/Cntr=.5,.3

Type RM Length L Ch R = 1 ,86799.31,518.04,519.29,634.49
BEGIN DESCRIPTION:
Copy of 421s3d.  XS 1/4, and 421s2 XS 4/4
Blocked WFSJ Trib 17.7 422s8u cross section between stations 6889.46 and 6908.87.  Manning's n = 0.01 due to flow over water in this area.  n=0.99 in ROB due to expansion from u/s XS 2/4
Set C/E at 0.6&0.8 to eliminate negative drawdown in 2%chance flow just d/s of 86216 bridge.
Bank Station offset =      -244
END DESCRIPTION:
XS GIS Cut Line= 6
     3154274.157    13944889.236     3152460.501    13938503.199
     3152687.391    13938295.482     3152779.102    13938021.909
     3152619.938    13937294.304     3150920.405    13932546.244
#Sta/Elev= 30
       0   85.68  517.18   87.26 1991.51   72.51  2198.2   80.23 2652.21   57.99
 4266.15   55.88    4493   47.99 4991.41   47.25 5031.47   40.04 5244.09   32.53
 5420.61   39.73  5433.2   45.65 5846.95   53.25 6191.73   45.88 6733.71   51.72
 6889.46   43.42 6908.87   43.61 7043.74   55.54 7218.26   58.15 7626.31   59.05
 7763.62   49.47 8003.27   58.66 8306.78   56.62 8943.68   52.53 9155.25   58.56
 11780.8   68.9612228.12   65.51   12728   70.9712801.67   78.6613032.41   81.44
#Mann= 8 ,-1 , 0
       0     .99       0  2198.2     .12       0 4991.41     .03       0
  5433.2     .12       0 6889.46     .01       0 6908.87     .12       0
 8306.78     .06       0 9155.25     .99       0
#Block Obstruct= 1 ,-1
 6889.46 6908.87   43.42
Bank Sta=4991.41,5433.2
XS Rating Curve= 0
Exp/Cntr=.8,.6

Type RM Length L Ch R = 1 ,86280.02,175.27,126.11,142.56
BEGIN DESCRIPTION:
421s2u, surveyed.  XS 3/4  Filtered points in cross section to 484 from 512. Filter tolerances:  used 0.05 ft for spacing and 0.001 for slope. Blocked WFSJ Trib 17.7 422s8u cross section between stations 6787.91 and 6807.32.  Manning's n set to 0.01 for flow over water.  NOTE:  Adding Trib 17.7's channel, added 4 more points to this cross section, bring the total number of points to 488.
Set C/E at 0.6&0.8 to remove negative drawdown in 2%chance flow just d/s of 86216 brdg
Bank Station offset =      -167
END DESCRIPTION:
XS GIS Cut Line= 6
      3154488.13    13944965.087     3154025.914    13942258.361
     3153349.118    13939549.817     3153002.497    13938598.329
     3152826.674     13937808.11     3150989.494     13932426.25
#Sta/Elev= 30
       0   85.83  528.98   88.99 1284.94    85.6 1615.14   76.85 2181.22   76.93
 2380.39   64.21 2800.16   55.44 3049.71   60.36 3101.05   54.81 3515.65   53.97
 3677.53    60.7 4960.58   47.88 5091.12   48.58 5102.12   40.44 5166.54   35.64
 5460.88   40.09 5539.05   53.02 5602.38   51.06 5840.44   43.72 6787.91   43.42
 6795.55   39.59 6807.32   43.61 6930.62   54.88 7024.01   55.93 7677.28    48.2
  7960.1   58.76 8880.84   53.98 9669.63   63.7212360.73   66.9613054.16    82.9
#Mann= 7 ,-1 , 0
       0     .99       0 2181.22     .12       0 4960.58     .04       0
 5602.38     .12       0 6787.91     .01       0 6807.32     .12       0
 9669.63     .99       0
#XS Ineff= 2 , 0
       0    4850   62.23    5750       0   62.23
Permanent Ineff=
       F       F
#Block Obstruct= 1 ,-1
 6787.91 6807.32   43.42
Bank Sta=5091.12,5539.05
XS Rating Curve= 0
Exp/Cntr=.8,.6

Type RM Length L Ch R = 3 ,86216.96,,,
BEGIN DESCRIPTION:
421s2  Southern Pacific RR
Made pier 11 4' diameter and pier 16 3' diameter consistent with estimate from photo.
Adjusted min. ch. invert of internal sections based on interpolation between nearest surveyed sections.
END DESCRIPTION:
Bridge Culvert--1,0,-1,-1, 0
Deck Dist Width WeirC Skew NumUp NumDn MinLoCord MaxHiCord MaxSubmerge Is_Ogee
54.56,17,2.6,0, 11, 11, , , .95, 0, 0,0,,
    1800 4974.99 4974.99 4990.81 5587.01 5618.36 5618.36    6435    6614    6826
   12500
   68.58   68.58   68.58   68.58    68.8    68.8    68.8   63.28   62.69   62.23
   62.23
       0       0   65.72   65.72   65.94   65.94       0       0       0       0
       0
    1800 4974.99 4974.99 4990.81 5587.01 5618.36 5618.36    6435    6614    6826
   12500
   68.58   68.58   68.58   68.58    68.8    68.8    68.8   63.28   62.69   62.23
   62.23
       0       0   65.72   65.72   65.94   65.94       0       0       0       0
       0
Pier Skew, UpSta & Num, DnSta & Num=  ,4991.99, 2 ,4991.99, 2 , 0 , 0 , 0 ,,
       1       1
      35   65.94
       1       1
      35   65.94
Pier Skew, UpSta & Num, DnSta & Num=  ,5008.69, 2 ,5008.69, 2 , 0 , 0 , 0 ,,
       1       1
      35   65.94
       1       1
      35   65.94
Pier Skew, UpSta & Num, DnSta & Num=  ,5025.59, 2 ,5025.59, 2 , 0 , 0 , 0 ,,
       1       1
      35   65.94
       1       1
      35   65.94
Pier Skew, UpSta & Num, DnSta & Num=  ,5042.59, 2 ,5042.59, 2 , 0 , 0 , 0 ,,
       1       1
      35   65.94
       1       1
      35   65.94
Pier Skew, UpSta & Num, DnSta & Num=  ,5058.65, 2 ,5058.65, 2 , 0 , 0 , 0 ,,
       1       1
      35   65.94
       1       1
      35   65.94
Pier Skew, UpSta & Num, DnSta & Num=  ,5074.92, 2 ,5074.92, 2 , 0 , 0 , 0 ,,
       1       1
      35   65.94
       1       1
      35   65.94
Pier Skew, UpSta & Num, DnSta & Num=  ,5092.25, 2 ,5092.25, 2 , 0 , 0 , 0 ,,
       1       1
      35   65.94
       1       1
      35   65.94
Pier Skew, UpSta & Num, DnSta & Num=  ,5108.32, 2 ,5108.32, 2 , 0 , 0 , 0 ,,
       1       1
      35   65.94
       1       1
      35   65.94
Pier Skew, UpSta & Num, DnSta & Num=  ,5125.47, 2 ,5125.47, 2 , 0 , 0 , 0 ,,
       1       1
      35   65.94
       1       1
      35   65.94
Pier Skew, UpSta & Num, DnSta & Num=  ,5139.06, 2 ,5139.06, 2 , 0 , 0 , 0 ,,
       4       4
      35   65.94
       4       4
      35   65.94
Pier Skew, UpSta & Num, DnSta & Num=  ,5214.98, 2 ,5214.98, 2 , 0 , 0 , 0 ,,
       4       4
      35   65.94
       4       4
      35   65.94
Pier Skew, UpSta & Num, DnSta & Num=  ,5247.56, 2 ,5247.56, 2 , 0 , 0 , 0 ,,
       1       1
      35   65.94
       1       1
      35   65.94
Pier Skew, UpSta & Num, DnSta & Num=  ,5279.69, 2 ,5279.69, 2 , 0 , 0 , 0 ,,
       1       1
      35   65.94
       1       1
      35   65.94
Pier Skew, UpSta & Num, DnSta & Num=  ,5312.15, 2 ,5312.15, 2 , 0 , 0 , 0 ,,
       1       1
      35   65.94
       1       1
      35   65.94
Pier Skew, UpSta & Num, DnSta & Num=  ,5345.72, 2 ,5345.72, 2 , 0 , 0 , 0 ,,
       1       1
      35   65.94
       1       1
      35   65.94
Pier Skew, UpSta & Num, DnSta & Num=  ,5376.22, 2 ,5376.22, 2 , 0 , 0 , 0 ,,
       3       3
      35   65.94
       3       3
      35   65.94
Pier Skew, UpSta & Num, DnSta & Num=  ,5408.68, 2 ,5408.68, 2 , 0 , 0 , 0 ,,
       1       1
      35   65.94
       1       1
      35   65.94
Pier Skew, UpSta & Num, DnSta & Num=  ,5438.34, 2 ,5438.34, 2 , 0 , 0 , 0 ,,
       1       1
      35   65.94
       1       1
      35   65.94
Pier Skew, UpSta & Num, DnSta & Num=  ,5468.43, 2 ,5468.43, 2 , 0 , 0 , 0 ,,
       1       1
      35   65.94
       1       1
      35   65.94
Pier Skew, UpSta & Num, DnSta & Num=  ,5498.18, 2 ,5498.18, 2 , 0 , 0 , 0 ,,
       1       1
      35   65.94
       1       1
      35   65.94
Pier Skew, UpSta & Num, DnSta & Num=  ,5528.53, 2 ,5528.53, 2 , 0 , 0 , 0 ,,
       1       1
      35   65.94
       1       1
      35   65.94
Pier Skew, UpSta & Num, DnSta & Num=  ,5558.32, 2 ,5558.32, 2 , 0 , 0 , 0 ,,
       1       1
      35   65.94
       1       1
      35   65.94
Pier Skew, UpSta & Num, DnSta & Num=  ,5588.36, 2 ,5588.36, 2 , 0 , 0 , 0 ,,
       1       1
      35   65.94
       1       1
      35   65.94
BR Coef=-1 , 1 , 1 ,1.05, 0 ,,,.8,0,1.25,0,
WSPro=,,,, 1 ,,,, 0 ,,,, 0 ,,,,-1 ,-1 ,-1 , 0 , 0 , 0 , 0 , 0
BR U #Sta/Elev= 30
       0   85.83  528.98   88.99 1284.94    85.6 1615.14   76.85 2181.22   76.93
 2380.39   64.21 2800.16   55.44 3049.71   60.36 3101.05   54.81 3515.65   53.97
 3677.53    60.7 4960.58   47.88 5091.12   48.12 5102.12   39.98 5166.54   35.18
 5460.88   39.63 5506.79   50.38 5602.38   51.06 5840.44   43.72 6787.91   43.42
 6795.55   39.59 6807.32   43.61 6930.62   54.88 7024.01   55.93 7677.28    48.2
  7960.1   58.76 8880.84   53.9810183.23   64.8312360.73   66.9613054.16    82.9
BR U #Mann= 7
       0     .99 2181.22     .12 4960.58     .03 5602.38     .12 6787.91     .01
 6807.32     .1210183.23     .99
BR D #Sta/Elev= 30
       0   85.91 1292.35   84.72 1966.62   66.95 2265.41   73.39    2529   54.93
  3626.5   53.63 3702.81   61.38 4309.94   53.91 4591.81    61.6 4969.87   42.72
 4997.88   48.12  5000.7   41.21 5109.67   35.18 5469.59   41.22  5515.5   52.56
 5547.76   44.73 5616.99   45.33 5645.51   43.42 5704.93   43.61  5778.9   59.86
 5977.51    63.4 6461.48   53.71 6528.09   43.97 6802.52   43.22 6946.28    57.1
 7246.62   61.22 9012.75   54.6710597.38   64.9912188.55      6412845.93   76.56
BR D #Mann= 7
       0     .99 2265.41     .12 4969.87     .03 5616.99     .12 5645.51     .01
 5704.93     .1210597.38     .99
BC Design=,, 0 ,, 0 ,,,,,,
BC HTab HWMax=88.99

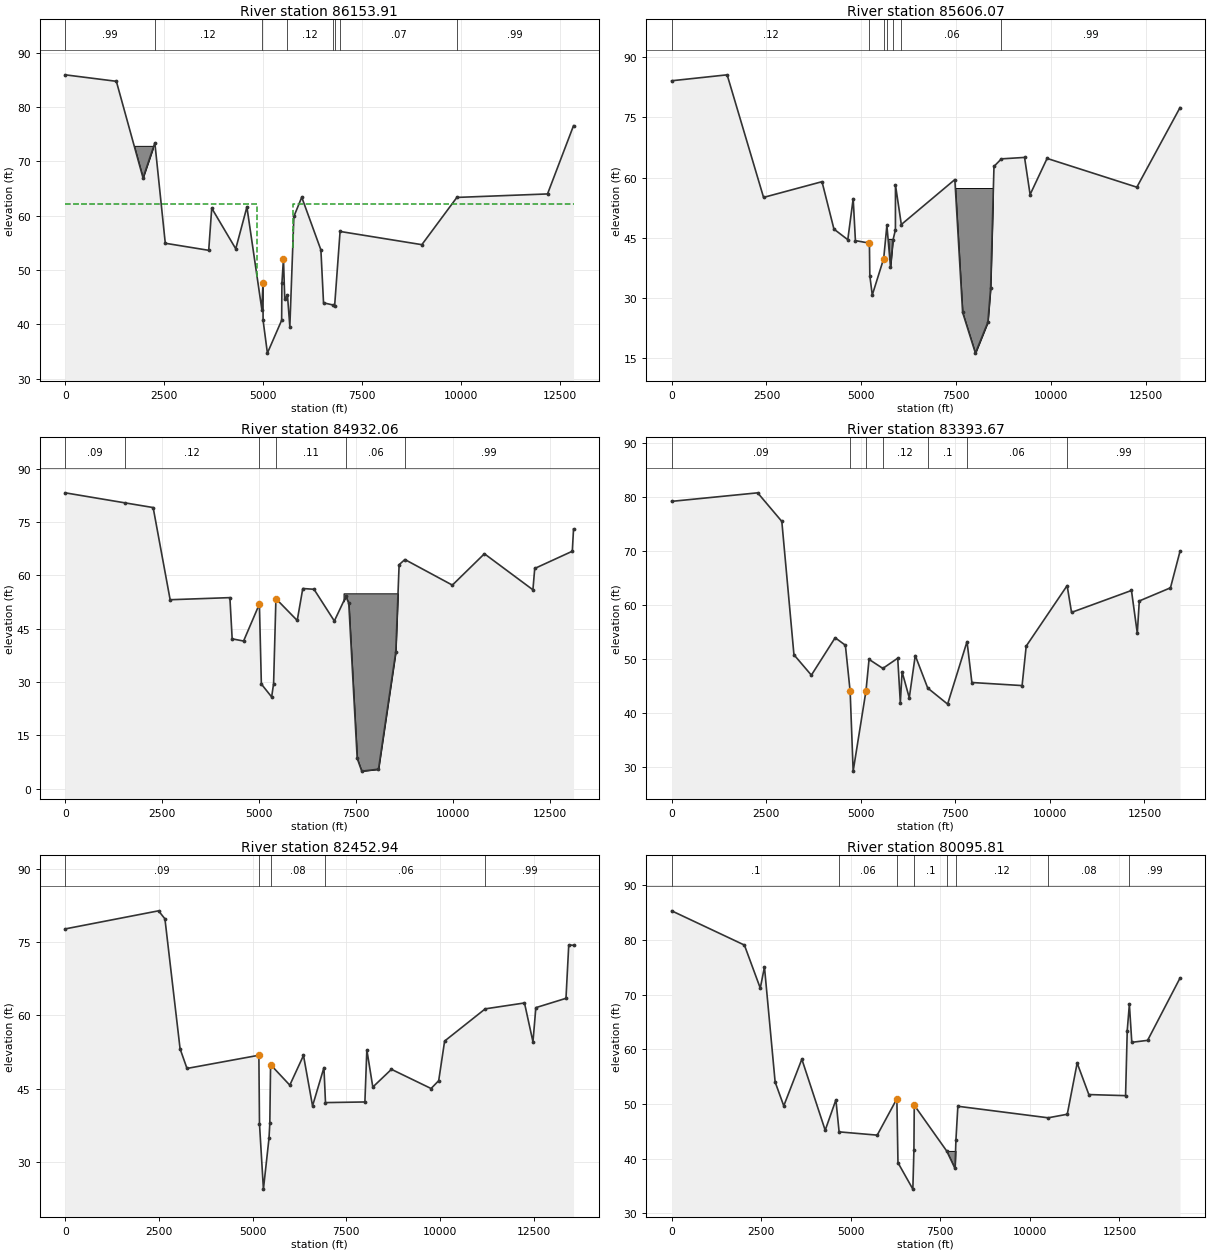
Type RM Length L Ch R = 1 ,86153.91,592.11,547.84,787.04
BEGIN DESCRIPTION:
Copy of 421s2u.  XS 2/4.
Filtered from 733 points to 496 points.  Used 0.5 ft for all filter tolerances and 0.015 as min. change in slope.  Adjusted elevn's based on nearest surveys u/s and d/s.
Blocked WFSJ Trib 17.7 422s8u cross section between stations 5645.51 and 5704.93.  Manning's n = 0.01 in this area.
Set C/E at 0.6&0.8 to remove negative drawdown in 2%chance flow just d/s of 86216 bridge
Bank Station offset =      -175
END DESCRIPTION:
XS GIS Cut Line= 6
     3154669.813    13944951.111     3154146.914    13942258.361
     3153790.765    13940602.455     3152750.132    13937337.116
     3152444.603    13936223.225     3151198.047    13932606.996
#Sta/Elev= 30
       0   85.91 1292.35   84.72 1966.62   66.95 2265.41   73.39    2529   54.93
  3626.5   53.63 3702.81   61.38 4309.94   53.91 4591.81    61.6 4969.87   42.72
 4997.88   47.66  5000.7   40.75 5109.67   34.72 5469.59   40.76 5476.42   47.56
  5515.5    52.1 5547.76   44.73 5616.99   45.33 5676.61   39.59  5778.9   59.86
 5977.51    63.4 6461.48   53.71 6528.09   43.97 6760.35   43.59 6808.11   43.35
 6946.28    57.1 9012.75   54.67 9897.53   63.3612188.55      6412845.93   76.56
#Mann= 8 ,-1 , 0
       0     .99       0 2265.41     .12       0 4969.87     .04       0
 5616.99     .12       0 6760.35     .01       0 6808.11     .12       0
 6946.28     .07       0 9897.53     .99       0
#XS Ineff= 2 , 0
       0    4850   62.23    5750       0   62.23
Permanent Ineff=
       F       F
#Block Obstruct= 2 ,-1
 6760.35 6844.17   43.59 1665.01 2217.15   72.85
Bank Sta=4997.88,5515.5
XS Rating Curve= 0
Exp/Cntr=.8,.6

Type RM Length L Ch R = 1 ,85606.07,862.4,674.01,398.29
BEGIN DESCRIPTION:
Copy of 421s2u.  XS 1/4.
Blocked WFSJ Trib 17.7 422v7 between stations 5650.71 and 5845.71.   Manning's n is set to 0.01 to represent flow over water in this area.  Edited survey elevn's based on nearest survey data.
Large pit in ROB is a large excavated area and was blocked to prevent storage.  The area further OB from pit will not effectively convey flow of the WFSJ and is assigned n = .99.
Bank Station offset =      -290
END DESCRIPTION:
XS GIS Cut Line= 6
      3154935.35     13945048.94     3154709.251    13943598.117
     3154054.071    13939513.982     3154237.295    13939279.863
     3154243.923    13938686.927     3152787.824    13931931.404
#Sta/Elev= 30
       0   84.15 1462.67   85.63 2423.36   55.07 3964.48   58.99 4279.47   47.17
 4644.46   44.53 4786.75   54.76  4845.6    44.3 5214.79   43.67 5225.79   35.53
 5290.21   30.73 5591.38   39.82 5675.71   48.11 5770.71   37.75 5835.71   44.39
 5900.71      47 5901.98   58.17 6056.26   48.31 7467.94   59.52 7672.65    26.4
  8010.2   16.25 8338.53   23.95 8411.42   32.39  8499.9    62.8 8695.12   64.68
 9306.19   65.04 9452.58   55.78 9900.55   64.7912267.64   57.6213405.62   77.45
#Mann= 7 ,-1 , 0
       0     .12       0 5214.79     .04       0 5591.38     .12       0
 5675.71     .01       0 5835.71     .12       0 6056.26     .06       0
 8695.12     .99       0
#Block Obstruct= 2 ,-1
 5650.71 5845.71   44.73 7467.94  8472.8   57.42
Bank Sta=5214.79,5591.38
XS Rating Curve= 0
Exp/Cntr=.3,.1

Type RM Length L Ch R = 1 ,84932.06,1513.96,1538.39,1671.73
BEGIN DESCRIPTION:
421v3
Large pit in ROB is an excavated area and was blocked  The further ROB will not effectively convey WFSJ flow and is assigned n = .99.
Bank Station offset =      -328
END DESCRIPTION:
XS GIS Cut Line= 6
     3155601.039    13944885.202     3155347.764    13942812.001
     3154855.133    13939945.788     3154645.533    13939518.525
     3153639.602    13933551.877     3153277.042    13931997.579
#Sta/Elev= 30
       0   83.19 1547.76   80.36 2269.75   79.05 2708.41   53.14 4250.51   53.73
 4309.22   42.14  4603.7   41.53  5011.7   51.92  5062.6   29.44 5327.98   25.81
 5378.36   29.54 5438.56   53.44 5988.07   47.31 6131.97   56.29 6421.02   56.08
  6946.3   47.16  7244.8   54.05 7318.48   52.17 7536.06    8.54 7653.09    4.96
 8085.56     5.5 8531.25    38.4 8618.12   62.99 8766.95   64.44 9992.31   57.25
10819.33   66.0612071.32   55.9312118.32   61.93 13087.9   66.7713119.64   73.02
#Mann= 6 ,-1 , 0
       0     .09       0 1547.76     .12       0  5011.7     .03       0
 5438.56     .11       0  7244.8     .06       0 8766.95     .99       0
#Block Obstruct= 1 ,-1
 7182.69 8590.45   54.94
Bank Sta=5011.7,5438.56
XS Rating Curve= 0
Exp/Cntr=.3,.1

Type RM Length L Ch R = 1 ,83393.67,832.75,940.73,774.28
BEGIN DESCRIPTION:
421v4  (Extended ROB)
Bank Station offset =       201
END DESCRIPTION:
XS GIS Cut Line= 6
      3156959.22     13944673.93     3156747.538    13942082.899
     3156380.956    13940848.523     3155682.233    13935743.716
     3154184.848    13933731.281 3153429.481398913931998.4320565
#Sta/Elev= 30
       0   79.26 2273.56   80.84  2912.3   75.55 3233.11   50.86 3693.69   47.08
 4322.91   54.01 4593.14   52.62 4719.29   44.07 4798.75   29.31 5137.82   44.17
 5218.89      50 5583.88   48.33 5977.28   50.22 6046.31   41.96 6092.67    47.7
 6282.51   42.89 6440.75   50.71  6770.6   44.69 7296.27   41.72 7809.81   53.29
 7937.96   45.72 9265.77   45.15 9374.56   52.4610456.71   63.6610573.04    58.7
12157.57   62.7612311.88   54.8412364.66   60.8213188.79   63.25   13441      70
#Mann= 7 ,-1 , 0
       0     .09       0 4719.29     .03       0 5137.82     .08       0
 5583.88     .12       0  6770.6      .1       0 7809.81     .06       0
10456.71     .99       0
Bank Sta=4719.29,5137.82
XS Rating Curve= 0
Exp/Cntr=.3,.1

Type RM Length L Ch R = 1 ,82452.94,2237.38,2357.13,3580.89
BEGIN DESCRIPTION:
421v5
Bank Station offset =      -288
END DESCRIPTION:
XS GIS Cut Line= 6
     3157230.856    13944583.385      3157313.34    13939605.343
     3156789.908    13938930.031     3155913.644    13935447.686
     3154351.963    13933681.195     3153624.132    13932057.943
#Sta/Elev= 30
       0   77.76 2489.33   81.47  2660.2   79.83 3064.68   53.15 3248.91   49.12
 5166.83   51.83 5182.92   37.75 5288.03   24.35 5437.05   34.81 5458.73   37.88
 5478.85    49.9 5991.54   45.69 6357.13   51.79  6598.7   41.43 6902.42   49.29
    6944   42.11 7995.27   42.24 8047.03   52.93 8206.43    45.3 8703.18   48.94
 9760.89      45 9963.97   46.61 10122.2   54.7411205.29   61.3512252.79   62.56
12479.01   54.5812555.83    61.613359.86   63.5113433.71   74.4713561.25   74.39
#Mann= 5 ,-1 , 0
       0     .09       0 5166.83     .03       0 5478.85     .08       0
    6944     .06       011205.29     .99       0
Bank Sta=5166.83,5478.85
XS Rating Curve= 0
Exp/Cntr=.3,.1

Type RM Length L Ch R = 1 ,80095.81,1621.32,1883.71,3226.86
BEGIN DESCRIPTION:
421v6  Blocked WFSJ Trib 16.8 423v7 to the cross section between stations 7676.4 and 7935.81.   Manning's n is set to 0.01 to represent flow over water in this area.
Bank Station offset =     -1733
END DESCRIPTION:
XS GIS Cut Line= 6
     3159403.945    13944387.203     3159376.738    13941901.981
     3159111.638     13938099.69     3158689.898    13937522.049
     3159113.253     13935967.89     3157575.019    13930628.266
#Sta/Elev= 30
       0    85.3 2030.45   79.04 2473.87   71.16 2590.23   75.04 2888.45      54
 3129.41   49.64 3634.23   58.18 4286.18   45.18 4585.16   50.74 4674.54   44.89
 5738.18   44.29 6286.93   50.93 6318.01   39.25 6733.27   34.42 6763.07   41.55
 6772.78   49.76  7676.4   41.41 7910.29    38.2 7935.81   43.37 7989.91   49.57
10511.04   47.4611044.53   48.1111320.78   57.4711646.73   51.7112672.12   51.51
12718.95   63.4212778.53   68.2212846.19   61.2613287.49   61.6214191.73      73
#Mann= 8 ,-1 , 0
       0      .1       0 4674.54     .06       0 6286.93     .03       0
 6772.78      .1       0  7676.4     .01       0 7935.81     .12       0
10511.04     .08       012778.53     .99       0
#Block Obstruct= 1 ,-1
  7676.4 7935.81   41.41
Bank Sta=6286.93,6772.78
XS Rating Curve= 0
Exp/Cntr=.3,.1