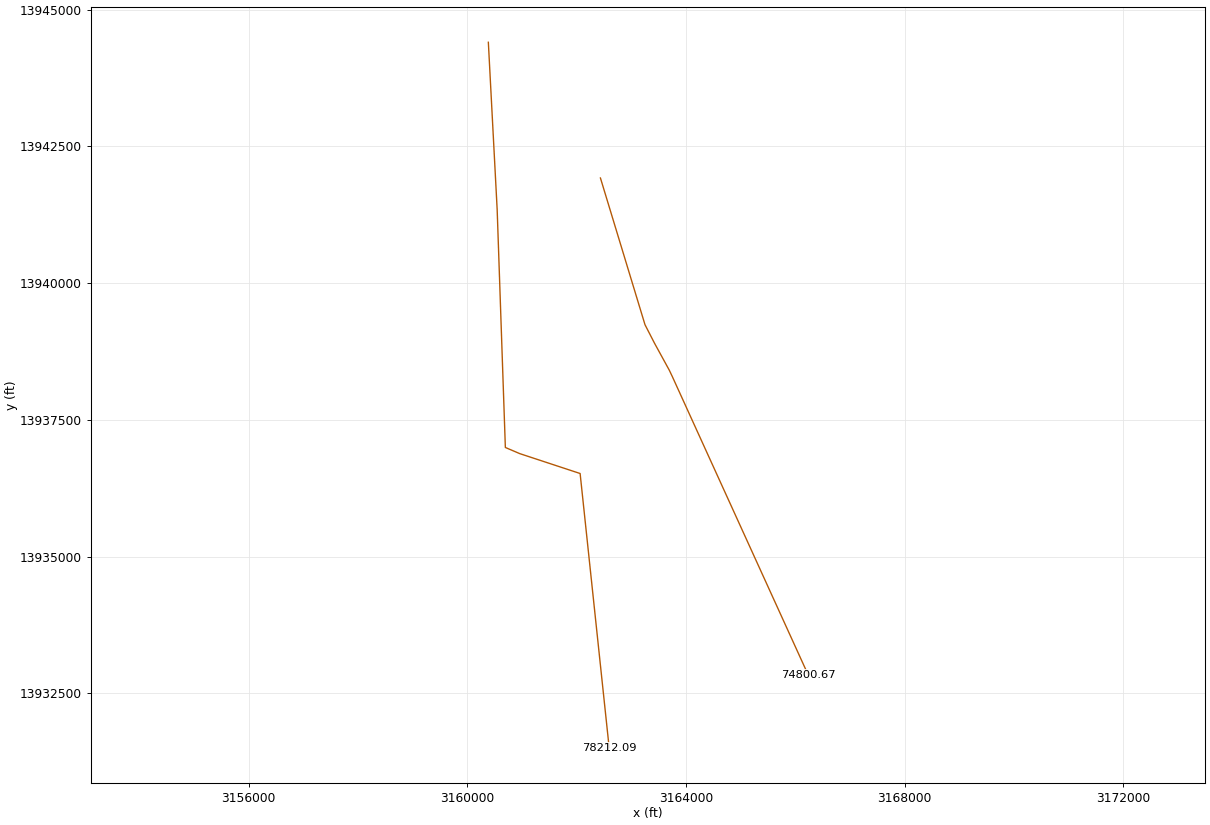
HEC-RAS study G103-00-00WFSJ.prj: G103-00-00WFSJ

--- G103-00-00WFSJ.g05 (geometry) --- (continued)

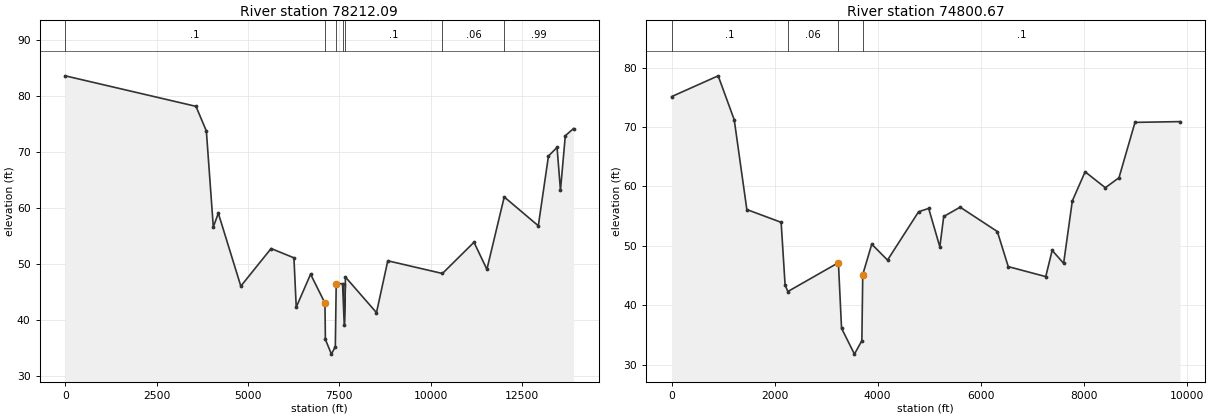
Type RM Length L Ch R = 1 ,78212.09,2701.43,3411.43,2677.24
BEGIN DESCRIPTION:
421v7 Blocked Jordon Gully 424v9 cross section between stations 7587 and 7667.   Manning's n is set to 0.01 to represent flow over water in this area.
Bank Station offset =     -2282
END DESCRIPTION:
XS GIS Cut Line= 6
     3160384.853    13944402.294      3160546.41    13941339.829
     3160696.124    13936994.089      3160959.37    13936881.636
      3162063.86    13936518.039     3162594.996     13931505.24
#Sta/Elev= 30
       0   83.68 3577.42   78.23 3861.43   73.83 4051.45   56.69 4188.89   59.14
 4804.32   46.12 5632.39   52.84 6257.19   51.18 6320.45   42.37 6712.62   48.25
 7106.01    43.1 7117.91    36.6 7282.22   33.98 7389.46   35.32 7413.83   46.53
    7587   46.57    7634   39.16    7667   47.74 8515.67   41.39 8824.57   50.65
10319.61   48.3811182.71   53.9611536.31   49.1212010.19   62.0512942.48    56.9
 13220.4   69.3613455.33    70.913548.67   63.2413681.04   72.9813906.09   74.27
#Mann= 7 ,-1 , 0
       0      .1       0 7106.01     .03       0 7413.83      .1       0
    7587     .01       0    7667      .1       010319.61     .06       0
12010.19     .99       0
#Block Obstruct= 1 ,-1
    7587    7667   46.57
Bank Sta=7106.01,7413.83
XS Rating Curve= 0
Exp/Cntr=.3,.1

Type RM Length L Ch R = 1 ,74800.67,2528.76,2016.1,1659.28
BEGIN DESCRIPTION:
421v8
Bank Station offset =      1451
END DESCRIPTION:
XS GIS Cut Line= 6
     3162435.325    13941920.981     3163250.575     13939238.82
     3163424.461    13938900.709     3163694.581    13938408.138
     3163749.464    13938292.593      3166237.03     13932834.09
#Sta/Elev= 30
       0   75.11  903.11    78.6 1215.01    71.2 1459.66   56.11 2125.85   53.96
 2202.77   43.41 2256.37   42.32 3237.96   47.17 3298.99   36.14 3549.42   31.79
 3693.52   34.06 3710.86   45.17 3885.48   50.28 4191.92   47.61 4795.15   55.74
 4990.92    56.3 5207.95   49.83  5283.1   54.94 5602.59   56.51 6324.58   52.41
 6536.43   46.51 7264.75   44.83 7389.32   49.24 7611.69   47.06  7780.7   57.56
 8029.14   62.46 8421.77   59.78  8686.9   61.46 8997.92   70.77 9871.83    70.9
#Mann= 4 ,-1 , 0
       0      .1       0 2256.37     .06       0 3237.96     .03       0
 3710.86      .1       0
Bank Sta=3237.96,3710.86
XS Rating Curve= 0
Exp/Cntr=.3,.1