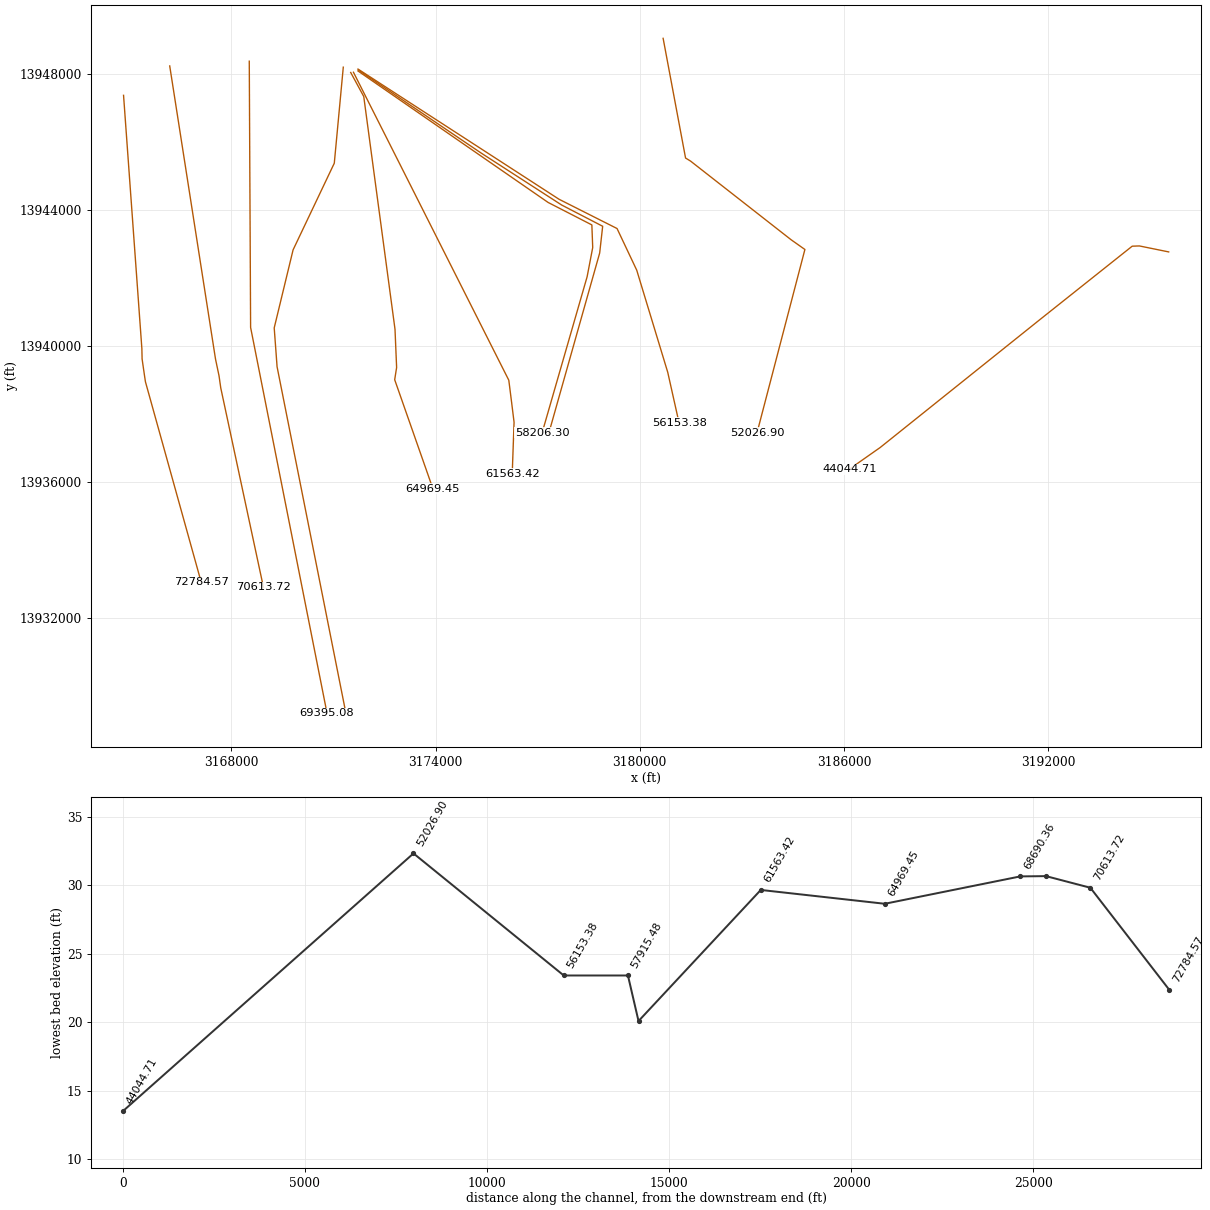
HEC-RAS study G103-00-00WFSJ.prj: G103-00-00WFSJ

--- G103-00-00WFSJ.g05 (geometry) --- (continued)

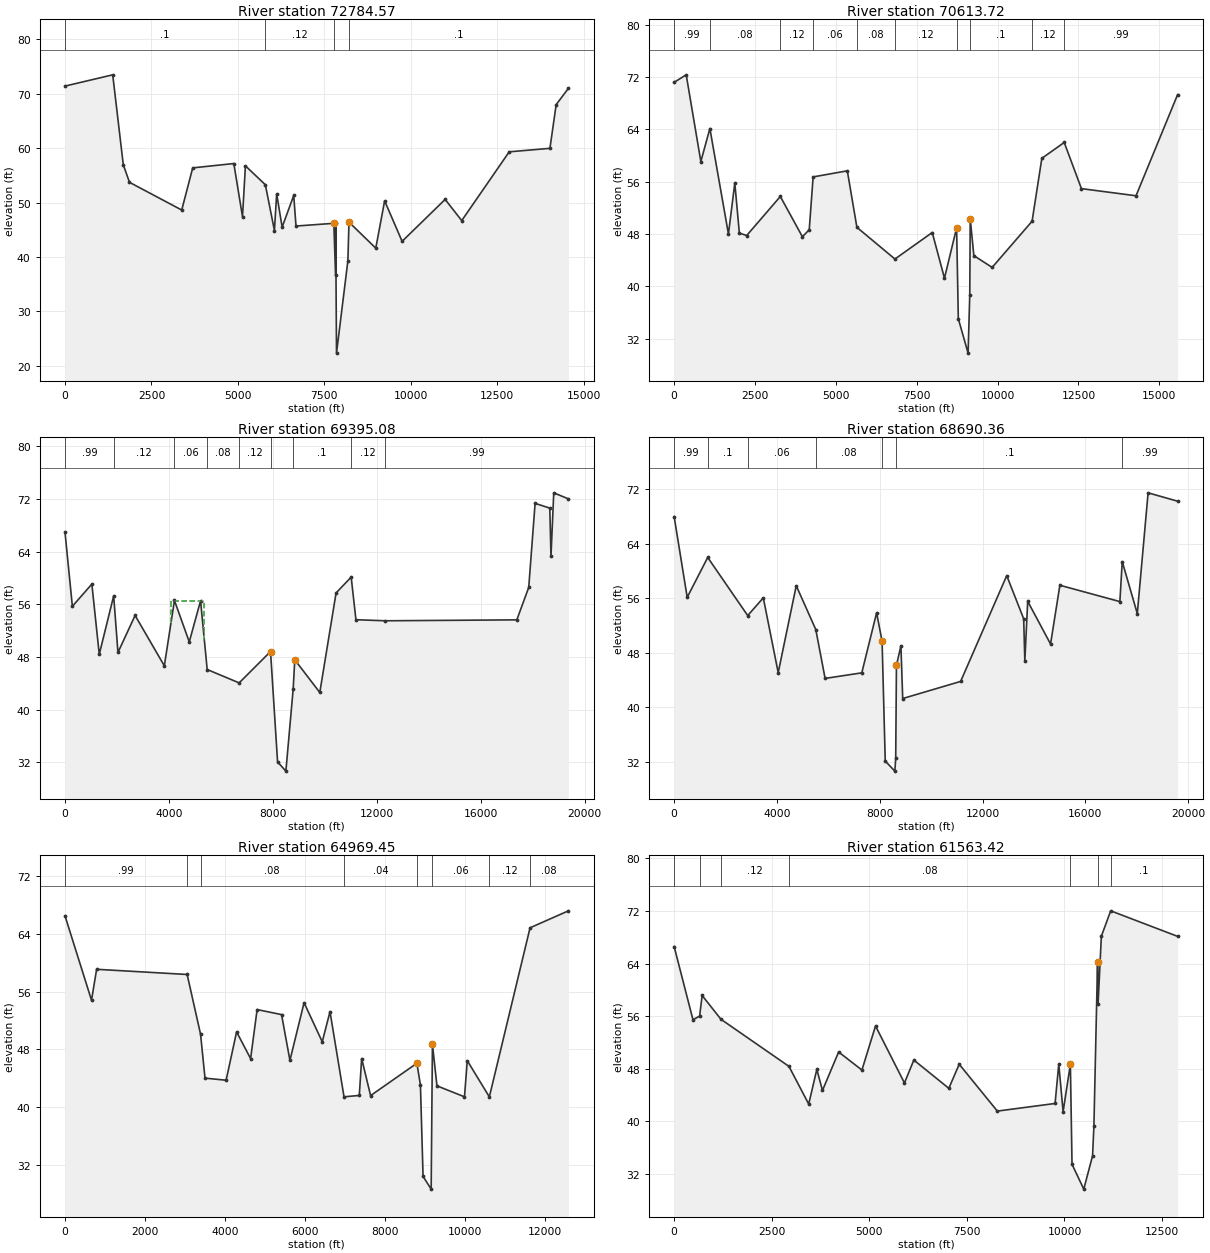
Type RM Length L Ch R = 1 ,72784.57,2066.5,2170.84,2108.01
BEGIN DESCRIPTION:
421v9
Bank Station offset =     -2850
END DESCRIPTION:
XS GIS Cut Line= 6
      3164833.89    13947360.299     3165372.148    13939917.658
     3165378.857    13939615.732     3165450.359    13939119.188
     3165477.138    13938943.642     3167115.165     13933056.09
#Sta/Elev= 30
       0   71.39  1380.3   73.46 1686.25   56.94 1864.82   53.72  3375.3   48.63
 3692.79   56.37 4881.54   57.17 5132.49    47.4  5216.6   56.75 5793.25   53.27
  6055.3   44.87 6120.14   51.59 6278.51   45.49 6613.08    51.3 6679.21   45.69
  7772.1   46.19 7822.89   36.62  7825.1   46.24 7850.18   22.35 8179.25   39.33
 8210.17   46.41 8985.19   41.63 9241.16   50.31  9746.7   42.8810989.97   50.58
11470.03   46.6912842.77   59.3214019.78   59.9614200.46   67.99 14554.5   70.98
#Mann= 4 ,-1 , 0
       0      .1       0 5793.25     .12       0  7772.1     .03       0
 8210.17      .1       0
Bank Sta=7772.1,8210.17
XS Rating Curve= 0
Exp/Cntr=.3,.1

Type RM Length L Ch R = 1 ,70613.72,1679,1218.64,1188
BEGIN DESCRIPTION:
421v10
 ROB and LOB were both greater than channel length due to the alignment of the d/s cross section.  Reduced ROB length 60 ft to = channel length.
Bank Station offset =     -4089
END DESCRIPTION:
XS GIS Cut Line= 6
     3166190.324    13948223.484      3167506.92    13939794.938
     3167535.843    13939611.759     3167639.124    13939119.188
     3167689.911    13938763.499     3168943.947    13932907.915
#Sta/Elev= 30
       0   71.18  372.86   72.32  825.17   59.08 1104.58   64.12 1678.67   48.01
 1875.32   55.81 2015.78   48.15 2242.45   47.78 3282.89   53.74 3965.97   47.59
 4177.04   48.67 4297.18   56.73 5354.15   57.66 5650.53   49.03 6826.79   44.19
 7980.23   48.24 8358.12   41.26 8733.17   48.94 8786.76   35.07  9088.5   29.82
 9140.58   38.77 9154.56   50.37 9266.39   44.71 9832.33   42.9111067.04   49.96
11369.24   59.5712061.09   61.9912593.19   54.9414281.34   53.8515567.14    69.3
#Mann= 10 ,-1 , 0
       0     .99       0 1104.58     .08       0 3282.89     .12       0
 4297.18     .06       0 5650.53     .08       0 6826.79     .12       0
 8733.17     .03       0 9154.56      .1       011067.04     .12       0
12061.09     .99       0
Bank Sta=8733.17,9154.56
XS Rating Curve= 0
Exp/Cntr=.3,.1

Type RM Length L Ch R = 1 ,69395.08,1650,704.72,800
XS GIS Cut Line= 3
  3168527.49386413948362.5380266 3168566.901454113940540.6977582
 3170812.968577113929201.9899799
#Sta/Elev= 30
       0      67     285    55.7 1035.01   59.07 1320.02    48.4 1875.03   57.28
 2040.03   48.69 2700.03   54.31 3825.04   46.66 4215.05   56.58 4785.05   50.29
 5220.06   56.54 5475.06    46.1 6705.07   44.07 7913.67   48.83 8184.38   32.08
 8504.23   30.67 8785.29   43.13 8846.46   47.58 9809.83   42.6110436.79   57.73
11017.87   60.1311201.37   53.6612332.95    53.517394.47   53.6417853.21   58.57
18097.87   71.3318663.65   70.6118709.53   63.3118816.56   72.9319381.03   72.01
#Mann= 9 ,-1 , 0
       0     .99       0 1875.03     .12       0 4215.05     .06       0
 5475.06     .08       0 6705.07     .12       0 7913.67     .03       0
 8785.29      .1       011017.87     .12       012332.95     .99       0
#XS Ineff= 1 ,-1
    4080    5370    56.5
Permanent Ineff=
       F
Bank Sta=7913.67,8846.46
XS Rating Curve= 0
Exp/Cntr=.3,.1

Type RM Length L Ch R = 1 ,68690.36,3506.66,3720.91,3394.91
BEGIN DESCRIPTION:
421v11
Bank Station offset =      3586
END DESCRIPTION:
XS GIS Cut Line= 6
      3171289.81    13948187.783     3171025.623    13945366.639
     3169814.882    13942819.907     3169260.354    13940527.776
     3169344.708     13939384.59       3171366.9    13929206.631
#Sta/Elev= 30
       0   68.01  507.62   56.17 1305.73   62.02 2861.56   53.49 3468.52   56.09
 4048.06   45.11 4750.25   57.87 5510.27   51.44 5872.86   44.26 7300.25   45.08
 7877.23    53.9 8089.59    49.7 8212.49   32.13 8586.92   30.65 8619.95   32.55
 8648.32   46.18 8822.29   49.04 8892.16   41.3111145.59   43.8212939.31   59.35
13598.97   53.0113643.04   46.8113755.07   55.5814644.08   49.3115006.73   57.94
17341.15   55.5417432.84   61.41 18018.8   53.7818439.18   71.5119587.38   70.28
#Mann= 7 ,-1 , 0
       0     .99       0 1305.73      .1       0 2861.56     .06       0
 5510.27     .08       0 8089.59     .03       0 8648.32      .1       0
17432.84     .99       0
Bank Sta=8089.59,8648.32
XS Rating Curve= 0
Exp/Cntr=.3,.1

Type RM Length L Ch R = 1 ,64969.45,3047.06,3406.03,3108.54
BEGIN DESCRIPTION:
421v12 (421v13 entered manually in model)
Bank Station offset =     -4159
END DESCRIPTION:
XS GIS Cut Line= 6
      3171507.96    13948030.869     3171890.992    13947326.225
     3172809.246    13940487.209     3172856.673    13939365.142
     3172800.077    13939004.809     3173924.785    13935796.583
#Sta/Elev= 30
       0   66.53   664.1   54.82  791.65   59.11 3055.87   58.39 3391.21   50.12
 3502.51   44.03 4030.67   43.74 4292.72   50.44 4643.12   46.73 4806.05   53.53
 5416.96   52.83 5626.68   46.49 5980.43   54.48 6435.02   49.06 6628.85   53.24
 6979.54   41.44 7361.55   41.63 7420.78   46.74 7644.27   41.61 8801.93   46.09
 8890.58   43.08 8956.73   30.41  9159.2   28.65 9190.69   48.72 9304.19   42.96
 9992.49   41.44 10062.2   46.4510614.39   41.4311632.63   64.8612592.17   67.21
#Mann= 8 ,-1 , 0
       0     .99       0 3055.87      .1       0 3391.21     .08       0
 6979.54     .04       0 8801.93     .03       0 9190.69     .06       0
10614.39     .12       011632.63     .08       0
Bank Sta=8801.93,9190.69
XS Rating Curve= 0
Exp/Cntr=.3,.1

Type RM Length L Ch R = 1 ,61563.42,3481.44,3357.11,1185.03
BEGIN DESCRIPTION:
421v15  (XS 4/4)
c/e coefficients of 0.5 and 0.7 are used to avoid negative changes in WSEL due to contraction from this section to the next d/s section 3/4 of bridge at which effective flow width is considerably narrowed.
Bank Station offset =     5493
END DESCRIPTION:
XS GIS Cut Line= 6
      3171588.45    13948038.291     3172553.354    13946128.029
     3176152.735    13938990.232     3176237.746    13938319.392
     3176307.177    13937755.937     3176253.188    13936237.062
#Sta/Elev= 30
       0   66.59  481.36   55.46  651.62   55.99  717.23   59.14 1198.41   55.52
 2940.81   48.35 3447.06   42.61 3655.13   47.89 3799.69   44.68 4213.48   50.54
 4810.45   47.79 5158.65    54.5 5899.98   45.82 6140.43   49.31 7036.41   45.01
 7302.93   48.67 8279.53   41.54 9758.65    42.7 9853.17   48.69  9964.2   41.45
10150.62   48.6710192.91   33.4410493.86   29.6610719.27   34.7410753.71    39.3
10847.35   64.29   10860   57.8210944.38   68.1611183.45   72.0312897.86   68.14
#Mann= 7 ,-1 , 0
       0     .12       0  651.62     .06       0 1198.41     .12       0
 2940.81     .08       010150.62     .03       010847.35     .12       0
11183.45      .1       0
Bank Sta=10150.62,10847.35
XS Rating Curve= 0
Exp/Cntr=.7,.5

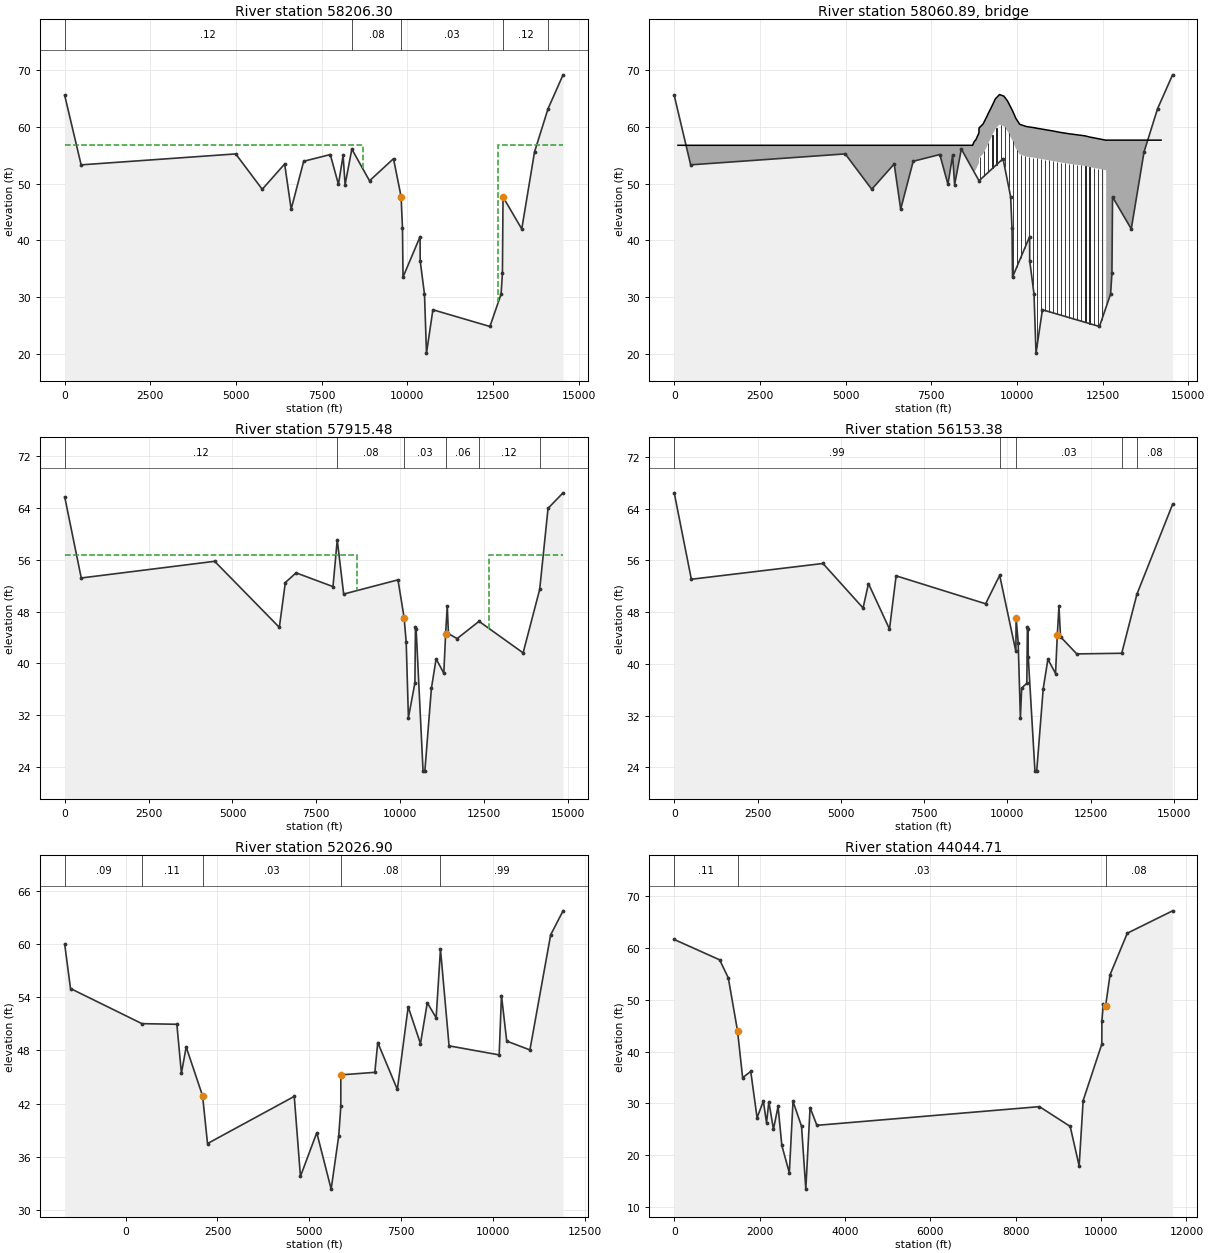
Type RM Length L Ch R = 1 ,58206.30,172.17,290.83,206.39
BEGIN DESCRIPTION:
421s1u, surveyed.  XS 3/4
Bank Station offset =     -5558
END DESCRIPTION:
XS GIS Cut Line= 6
       3171722.9    13948075.271     3177307.202    13944213.268
     3178593.017    13943552.976     3178617.966     13942887.66
     3178453.704    13942030.277     3177131.724    13937447.255
#Sta/Elev= 30
       0   65.54  479.53   53.29  4990.5   55.22 5764.79   48.98 6418.94   53.44
 6608.91   45.47 6974.48   53.92 7750.67   55.11 7988.48   49.85 8124.73   54.95
  8183.2   49.79 8379.29   56.07 8895.74   50.48 9595.58   54.38 9817.13   47.69
  9857.8   42.14 9873.39    33.510372.11   40.6310373.78    36.410500.01   30.47
10558.47   20.0810745.25   27.7312409.34   24.7812735.18   30.4912774.28   34.16
12792.02   47.6213338.94   41.9813711.06   55.5614105.39   63.19 14543.9   69.17
#Mann= 5 ,-1 , 0
       0     .12       0 8379.29     .08       0 9817.13     .03       0
12792.02     .12       014105.39      .1       0
#XS Ineff= 2 , 0
       0    8700   56.74   12650       0   56.74
Permanent Ineff=
       F       F
Bank Sta=9817.13,12792.02
XS Rating Curve= 0
Exp/Cntr=.5,.3

Type RM Length L Ch R = 3 ,58060.89,,,
BEGIN DESCRIPTION:
421s1  West Lake Houston Parkway
END DESCRIPTION:
Bridge Culvert--1,0,-1,-1, 0
Deck Dist Width WeirC Skew NumUp NumDn MinLoCord MaxHiCord MaxSubmerge Is_Ogee
117.91,55,2.6,0, 31, 31, , , .95, 0, 0,0,,
   108.5 8706.82 8755.72 8755.72 8800.13 8892.94 8894.75  9013.9 9133.63 9151.19
 9248.15  9372.2 9491.85 9619.44 9726.78 9849.56  9870.6  9972.110082.4510268.47
 10550.110551.14 11048.6 11273.311526.41 11983.912115.3112605.9512605.9512614.83
 14208.5
   56.74   56.74   57.42   57.42   57.68   58.92   59.79    60.5   61.94   62.19
   63.35   64.93   65.69   65.42   64.56   63.11   62.87   61.47   60.45   60.06
    59.8   59.78   59.27   59.01   58.77   58.41   58.21   57.63   57.63   57.65
   57.65
       0       0       0   52.12   52.38   53.62   54.49    55.2   56.64   56.89
   58.05   59.63   60.39   60.12   59.26   57.81   57.57   56.17   55.15   54.76
    54.5   54.48   53.97   53.71   53.47   53.11   52.91   52.33       0       0
       0
   108.5 8706.82 8755.72 8755.72 8800.13 8892.94 8894.75  9013.9 9133.63 9151.19
 9248.15  9372.2 9491.85 9619.44 9726.78 9849.56  9870.6  9972.110082.4510268.47
 10550.110551.14 11048.6 11273.311526.41 11983.912115.3112605.9512605.9512614.83
   14250
   56.74   56.74   57.42   57.42   57.68   58.92   59.79    60.5   61.94   62.19
   63.35   64.93   65.69   65.42   64.56   63.11   62.87   61.47   60.45   60.06
    59.8   59.78   59.27   59.01   58.77   58.41   58.21   57.63   57.63   57.65
   57.65
       0       0       0   52.12   52.38   53.62   54.49    55.2   56.64   56.89
   58.05   59.63   60.39   60.12   59.26   57.81   57.57   56.17   55.15   54.76
    54.5   54.48   53.97   53.71   53.47   53.11   52.91   52.33       0       0
       0
Pier Skew, UpSta & Num, DnSta & Num=  ,8934.46, 2 ,8934.46, 2 , 0 , 0 , 0 ,,
       3       3
      20   60.39
       3       3
      20   60.39
Pier Skew, UpSta & Num, DnSta & Num=  ,9052.33, 2 ,9052.33, 2 , 0 , 0 , 0 ,,
       3       3
      20   60.39
       3       3
      20   60.39
Pier Skew, UpSta & Num, DnSta & Num=  ,9170.22, 2 ,9170.22, 2 , 0 , 0 , 0 ,,
       3       3
      20   60.39
       3       3
      20   60.39
Pier Skew, UpSta & Num, DnSta & Num=  ,9287.94, 2 ,9287.94, 2 , 0 , 0 , 0 ,,
       3       3
      20   60.39
       3       3
      20   60.39
Pier Skew, UpSta & Num, DnSta & Num=  ,9405.59, 2 ,9405.59, 2 , 0 , 0 , 0 ,,
       3       3
      20   60.39
       3       3
      20   60.39
Pier Skew, UpSta & Num, DnSta & Num=  ,9523.89, 2 ,9523.89, 2 , 0 , 0 , 0 ,,
       3       3
      20   60.39
       3       3
      20   60.39
Pier Skew, UpSta & Num, DnSta & Num=  ,9641.82, 2 ,9641.82, 2 , 0 , 0 , 0 ,,
       3       3
      20   60.39
       3       3
      20   60.39
Pier Skew, UpSta & Num, DnSta & Num=  ,9759.79, 2 ,9759.79, 2 , 0 , 0 , 0 ,,
       3       3
      20   60.39
       3       3
      20   60.39
Pier Skew, UpSta & Num, DnSta & Num=  ,9879.21, 2 ,9879.21, 2 , 0 , 0 , 0 ,,
       3       3
      20   60.39
       3       3
      20   60.39
Pier Skew, UpSta & Num, DnSta & Num=  ,9998.39, 2 ,9998.39, 2 , 0 , 0 , 0 ,,
       3       3
      20   60.39
       3       3
      20   60.39
Pier Skew, UpSta & Num, DnSta & Num=  ,10114.08, 2 ,10114.08, 2 , 0 , 0 , 0 ,,
       3       3
      20   60.39
       3       3
      20   60.39
Pier Skew, UpSta & Num, DnSta & Num=  ,10231.69, 2 ,10231.69, 2 , 0 , 0 , 0 ,,
       3       3
      20   60.39
       3       3
      20   60.39
Pier Skew, UpSta & Num, DnSta & Num=  ,10350.24, 2 ,10350.24, 2 , 0 , 0 , 0 ,,
       3       3
      20   60.39
       3       3
      20   60.39
Pier Skew, UpSta & Num, DnSta & Num=  ,10467.05, 2 ,10467.05, 2 , 0 , 0 , 0 ,,
       3       3
      20   60.39
       3       3
      20   60.39
Pier Skew, UpSta & Num, DnSta & Num=  ,10585.6, 2 ,10585.6, 2 , 0 , 0 , 0 ,,
       3       3
      20   60.39
       3       3
      20   60.39
Pier Skew, UpSta & Num, DnSta & Num=  ,10703.98, 2 ,10703.98, 2 , 0 , 0 , 0 ,,
       3       3
      20   60.39
       3       3
      20   60.39
Pier Skew, UpSta & Num, DnSta & Num=  ,10822, 2 ,10822, 2 , 0 , 0 , 0 ,,
       3       3
      20   60.39
       3       3
      20   60.39
Pier Skew, UpSta & Num, DnSta & Num=  ,10940.14, 2 ,10940.14, 2 , 0 , 0 , 0 ,,
       3       3
      20   60.39
       3       3
      20   60.39
Pier Skew, UpSta & Num, DnSta & Num=  ,11058.42, 2 ,11058.42, 2 , 0 , 0 , 0 ,,
       3       3
      20   60.39
       3       3
      20   60.39
Pier Skew, UpSta & Num, DnSta & Num=  ,11175.83, 2 ,11175.83, 2 , 0 , 0 , 0 ,,
       3       3
      20   60.39
       3       3
      20   60.39
Pier Skew, UpSta & Num, DnSta & Num=  ,11293.6, 2 ,11293.6, 2 , 0 , 0 , 0 ,,
       3       3
      20   60.39
       3       3
      20   60.39
Pier Skew, UpSta & Num, DnSta & Num=  ,11411.45, 2 ,11411.45, 2 , 0 , 0 , 0 ,,
       3       3
      20   60.39
       3       3
      20   60.39
Pier Skew, UpSta & Num, DnSta & Num=  ,11529.59, 2 ,11529.59, 2 , 0 , 0 , 0 ,,
       3       3
      20   60.39
       3       3
      20   60.39
Pier Skew, UpSta & Num, DnSta & Num=  ,11646.53, 2 ,11646.53, 2 , 0 , 0 , 0 ,,
       3       3
      20   60.39
       3       3
      20   60.39
Pier Skew, UpSta & Num, DnSta & Num=  ,11765.25, 2 ,11765.25, 2 , 0 , 0 , 0 ,,
       3       3
      20   60.39
       3       3
      20   60.39
Pier Skew, UpSta & Num, DnSta & Num=  ,11882.66, 2 ,11882.66, 2 , 0 , 0 , 0 ,,
       3       3
      20   60.39
       3       3
      20   60.39
Pier Skew, UpSta & Num, DnSta & Num=  ,12002.5, 2 ,12002.5, 2 , 0 , 0 , 0 ,,
       3       3
      20   60.39
       3       3
      20   60.39
Pier Skew, UpSta & Num, DnSta & Num=  ,12119.87, 2 ,12119.87, 2 , 0 , 0 , 0 ,,
       3       3
      20   60.39
       3       3
      20   60.39
Pier Skew, UpSta & Num, DnSta & Num=  ,12237.75, 2 ,12237.75, 2 , 0 , 0 , 0 ,,
       3       3
      20   60.39
       3       3
      20   60.39
Pier Skew, UpSta & Num, DnSta & Num=  ,12355.22, 2 ,12355.22, 2 , 0 , 0 , 0 ,,
       3       3
      20   60.39
       3       3
      20   60.39
Pier Skew, UpSta & Num, DnSta & Num=  ,12472.97, 2 ,12472.97, 2 , 0 , 0 , 0 ,,
       3       3
      20   60.39
       3       3
      20   60.39
BR Coef=-1 , 1 , 1 ,1.05, 0 ,,,.8,0,1.25,0,
WSPro=,,,, 1 ,,,, 0 ,,,, 0 ,,,,-1 ,-1 ,-1 , 0 , 0 , 0 , 0 , 0
BC Design=,, 0 ,, 0 ,,,,,,
BC HTab HWMax=69.17

Type RM Length L Ch R = 1 ,57915.48,1311.81,1762.1,3419.65
BEGIN DESCRIPTION:
421s1d, surveyed.  XS 2/4
Bank Station offset =     -5735
END DESCRIPTION:
XS GIS Cut Line= 6
      3171729.02    13948106.133     3175331.586    13945669.856
     3177703.777    13944138.619     3178910.457    13943513.642
     3178822.793    13942728.669     3177319.871    13937405.445
#Sta/Elev= 30
       0   65.67  492.89   53.17 4469.68   55.74 6397.86   45.56  6576.5   52.47
 6897.81   53.96 7996.91   51.84 8124.18   59.04 8315.28   50.69  9934.3   52.88
 10116.4   47.08 10179.4   43.2810245.37   31.6410439.02      3710455.33   45.68
10475.21   45.3210681.38   23.4910735.32   23.4110930.76   36.1611071.28   40.71
11300.69    38.511353.85   44.4911403.34   48.8911438.06   44.5911697.13   43.83
12350.42   46.4913664.53   41.6314158.91   51.4114407.57    63.914855.21   66.29
#Mann= 6 ,-1 , 0
       0     .12       0 8124.18     .08       0 10116.4     .03       0
11353.85     .06       012350.42     .12       014158.91     .08       0
#XS Ineff= 2 , 0
       0    8700   56.74   12649       0   56.74
Permanent Ineff=
       F       F
Bank Sta=10116.4,11353.85
XS Rating Curve= 0
Exp/Cntr=.5,.3

Type RM Length L Ch R = 1 ,56153.38,3488.67,4126.47,5040.6
BEGIN DESCRIPTION:
Copy of 421s1d.  XS 1/4.
Bank Station offset =     -5881
END DESCRIPTION:
XS GIS Cut Line= 6
      3171722.33    13948131.701     3177629.127     13944306.58
     3179332.809    13943446.955     3179910.763    13942224.359
     3180822.152    13939223.443     3181155.588    13937734.099
#Sta/Elev= 30
       0   66.43  513.79   53.07 4464.51   55.51 5668.75   48.63  5831.3    52.4
 6462.31   45.37 6660.45    53.6 9347.34   49.28 9769.73   53.6710256.37   41.91
10262.71   47.0810325.71   43.2810391.68   31.6410430.25   36.2410585.33      37
10601.64   45.6810621.52   45.3210627.22   41.1210827.69   23.4910881.63   23.41
11077.07   36.1611217.59   40.71   11447    38.511500.16   44.4911549.65   48.89
11596.68   44.1712085.01   41.5313433.69   41.6313890.29   50.7714960.22   64.65
#Mann= 5 ,-1 , 0
       0     .99       0 9769.73     .12       010262.71     .03       0
13433.69     .12       013890.29     .08       0
Bank Sta=10262.71,11500.16
XS Rating Curve= 0
Exp/Cntr=.3,.1

Type RM Length L Ch R = 1 ,52026.90,14114.78,7982.19,6760.16
BEGIN DESCRIPTION:
421v16  (Extended LOB)
Bank Station offset =      -595
The far ROB area is not blocked.  Based on the aerial and LIDAR, backwater or ineffective flow will enter this area.
END DESCRIPTION:
XS GIS Cut Line= 6
      3180686.72    13949034.764     3181345.717    13945518.568
     3181492.333    13945428.456     3184446.915     13943117.21
     3184851.979    13942831.283     3183445.176    13937445.122
#Sta/Elev= 30
   -1657      60   -1499      55  445.25   51.03 1395.31   50.96 1519.48   45.43
  1649.2   48.39 2095.52   42.87 2229.84   37.48 4590.42   42.81 4758.97   33.77
 5203.53   38.71 5594.82   32.33 5801.28   38.36 5857.59   41.67 5858.08   45.24
 6783.53   45.53 6862.95    48.9  7396.1   43.59 7691.18   52.93 8025.34   48.77
 8211.41   53.39 8452.55   51.69 8569.89   59.45 8804.23   48.5210167.39    47.5
10230.19   54.2110373.07   49.0611004.32   48.0611568.51   61.0611906.36   63.78
#Mann= 5 ,-1 , 0
   -1657     .09       0  445.25     .11       0 2095.52     .03       0
 5858.08     .08       0 8569.89     .99       0
Bank Sta=2095.52,5858.08
XS Rating Curve= 0
Exp/Cntr=.3,.1

Type RM Length L Ch R = 1 ,44044.71,0,0,0
BEGIN DESCRIPTION:
lh8p67
Bank Station offset =     18517
Section 44044.71 is a common section to Lake Houston RS 48519.40 (lh8p67), so the survey data are used in that section.
END DESCRIPTION:
XS GIS Cut Line= 6
     3195539.716    13942759.906     3194677.891    13942935.463
     3194467.725    13942927.962     3191748.696     13940765.22
     3187065.105    13937014.407     3186155.401    13936376.018
#Sta/Elev= 30
       0   61.58 1064.14   57.66 1267.01   54.18 1482.83   43.98 1602.83   34.96
 1792.83   36.16 1940.83   27.25 2088.83   30.44 2162.83   26.24 2216.83   30.33
 2324.83   25.03 2432.83   29.42 2520.83   21.92 2696.83   16.61 2782.83    30.4
 2982.83    25.6 3082.83   13.49 3182.83   29.19 3342.83   25.78 8556.83   29.38
 9276.83   25.57 9486.83   17.96 9580.83   30.5610017.83   41.4310019.83   45.83
10052.83   49.2210107.83   48.8210210.78   54.7810615.13   62.7911675.83    67.1
#Mann= 3 , 0 , 0
       0     .11       0 1482.83     .03       010107.83     .08       0
Bank Sta=1482.83,10107.83
XS Rating Curve= 0
Exp/Cntr=.3,.1

Chan Stop Cuts=-1

--- G103-00-00WFSJ.g03 (geometry) ---

Geom Title=LOMR 08-06-0712P Geo
Version=Version 3.0.1  Mar 2001

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